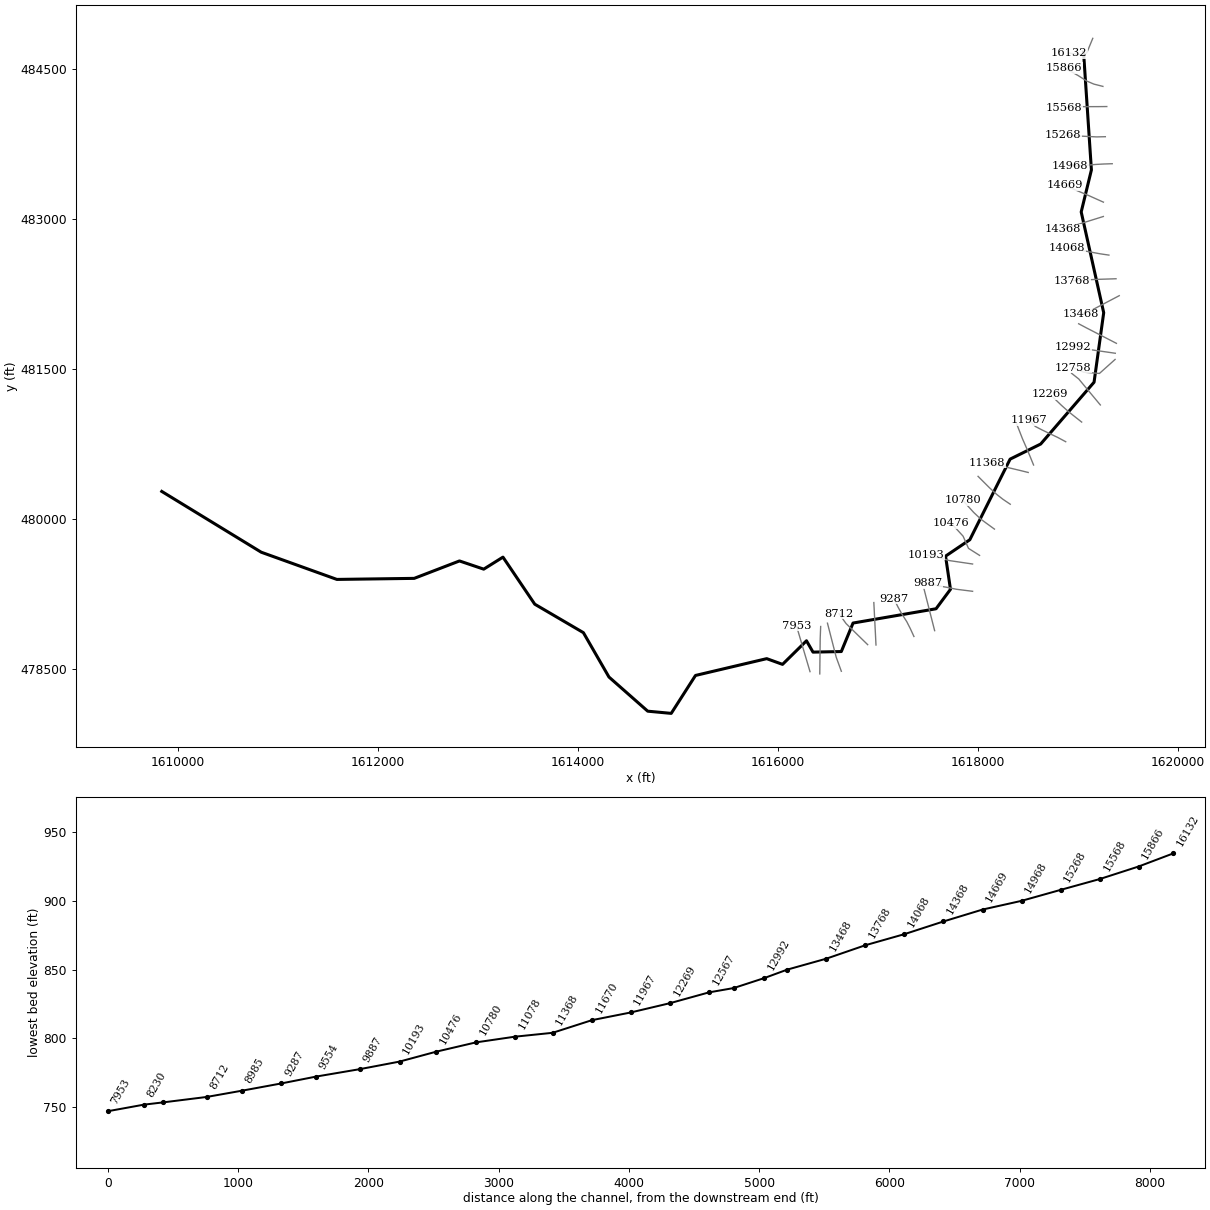
--- BgTrbbleCk.prj (project) ---

Proj Title=BgTrbbleCk
Current Plan=p01
Default Exp/Contr=0,0
English Units
Geom File=g01
Flow File=f01
Plan File=p01
BEGIN DESCRIPTION:
---------- MODELED AS PART OF WVEM CTP PROGRAM, 2025----------
Stream Name: Big Tribble Creek
Flood Zone: AFH
Marshall County, WV
HEC-RAS Version: RAS 6.6
Vertical Datum: NAVD88
Projection: NAD 1983 StatePlane West Virginia N FIPS 4701 (US Feet)
Terrain: 1-meter West Virginia FEMA R3 South Central (collected 2018-2019)
Land Use: 2024 NLCD
Hydrologic Method:
Duda et al., "Estimation of magnitude and frequency of floods for rural, unregulated streams in and near Virginia and West Virginia." September 8, 2025.
Additional Model Notes:
None
END DESCRIPTION:
DSS Export Rating Curves= 0
DSS Export Rating Curve Sorted= 0
DSS Export Volume Flow Curves= 0
DXF OffsetX= 0
DXF OffsetY= 0
DXF ScaleX= 0
DXF ScaleY= 0

--- BgTrbbleCk.p01 (plan) ---

Plan Title=Floodplain
Program Version=6.60
Short Identifier=Floodplain
Geom File=g01
Flow File=f01
Subcritical Flow
K Sum by GR= 0
Std Step Tol= 0.01
Critical Tol= 0.01
Num of Std Step Trials= 20
Max Error Tol= 0.3
Flow Tol Ratio= 0.001
Split Flow NTrial= 30
Split Flow Tol= 0.02
Split Flow Ratio= 0.02
Log Output Level= 0
Friction Slope Method= 1
Unsteady Friction Slope Method= 2
Unsteady Bridges Friction Slope Method= 1
Parabolic Critical Depth
Global Vel Dist= 0 , 0 , 0
Global Log Level= 0
CheckData=False
Encroach Param=-1 ,0,0, 0
Flow Ratio Tolerance=0.1
Flow Ratio Min Ratio=0.5
Flow Ratio Max Ratio=4
Flow Ratio Max Iterations= 10
Mapping Interval=1HOUR
Computation Time Step Use Courant=        0
Computation Time Step Use Time Series=    0
Computation Time Step Count To Double=0
Computation Time Step Max Doubling=0
Computation Time Step Max Halving=0
Computation Time Step Residence Courant=0
Run HTab= 0
Run UNet= 0
Run Sediment= 0
Run PostProcess= 0
Run WQNet= 0
Run RASMapper=-1
UNET Theta= 0
UNET Theta Warmup= 0
UNET ZTol= 0
UNET ZSATol= 0
UNET MxIter= 0
UNET Max Iter WO Improvement= 0
UNET MaxInSteps= 0
UNET DtIC= 0
UNET DtMin= 0
UNET MaxCRTS= 0
UNET WFStab= 0
UNET SFStab= 0
UNET WFX= 1
UNET SFX= 1
UNET Gravity=32.17405
UNET 1D Methodology=Finite Difference
UNET DSS MLevel= 1
UNET Pardiso=0
UNET DZMax Abort= 0
UNET Use Existing IB Tables= 0
UNET Froude Reduction=False
UNET Froude Limit= 0
UNET Froude Power= 0
UNET D1 Cores= 0
UNET WindReference=Eulerian
UNET WindDragFormulation=Hsu (1988)
UNET D2 Coriolis=0
UNET D2 Cores= 0
UNET D2 Theta= 1
UNET D2 Theta Warmup= 1
UNET D2 Z Tol= 0.01
UNET D2 Volume Tol= 0.01
UNET D2 Max Iterations= 20
UNET D2 Advanced Convergence=0
UNET D2 WS Max Tol=0.15
UNET D2 WS RMS Tol=0.002
UNET D2 WS Stall Tol=1
UNET D2 Equation= 0
UNET D2 RampUpFraction=0.1
UNET D2 TimeSlices= 1
UNET D2 Turbulence Formulation=Non-Conservative (original)
UNET D2 Eddy Viscosity=0.3
UNET D2 Transverse Eddy Viscosity=0.1
UNET D2 Smagorinsky Mixing=0
UNET D2 BCVolumeCheck=0
UNET D2 Cores=0
UNET D2 SolverType=PARDISO (Direct)
UNET D2 Minimum Iterations= 3
UNET D2 Maximum Iterations= 30
UNET D2 Restart Number= 10
UNET D2 Relaxation Coeff=1.3
UNET D2 SOR Precondition Iterations= 10
UNET D2 ILUT Maximum Fill= 8
UNET D2 ILUT Tolerance=1E-08
UNET D2 Convergence Tolerance=0.00001
PS Theta= 1
PS WS Tol= 0.01
PS Volume Tol= 0.01
PS Max Iterations= 20
PS Equation= 0
PS Advance Time Step=-1
PS Target Courant=0.9
PS Time Slices= 1
PS Iterate With 2D=0
PS Project Initial WSE from DS=-1
PS Ramp Up Initial WSE from US=-1
PS Cores=0
UNET D1D2 MaxIter= 0
UNET D1D2 ZTol=0.01
UNET D1D2 QTol=0.1
UNET D1D2 MinQTol=1
Write IC File= 0
Write IC File at Fixed DateTime=0
Write IC File at Sim End=0
Echo Input=False
Echo Parameters=False
Echo Output=False
Write Detailed= 0
HDF Write Warmup=0
HDF Write Time Slices=0
HDF Flush=0
HDF Compression= 1
HDF Chunk Size= 1
HDF Spatial Parts= 1
HDF Use Max Rows=0
HDF Fixed Rows= 1
Calibration Method= 0
Calibration Iterations= 20
Calibration Max Change=0.05
Calibration Tolerance=0.2
Calibration Maximum=1.5
Calibration Minimum=0.5
Calibration Optimization Method= 1
WQ AD Non Conservative
WQ ULTIMATE=-1
WQ Max Comp Step=1HOUR
WQ Output Interval=15MIN
WQ Output Selected Increments= 0
WQ Create Restart=0
WQ Fixed Restart=0
WQ System Summary=0
WQ Write To DSS=0
Sorting and Armoring Iterations= 10
XS Update Threshold= 0.02
Bed Roughness Predictor= 0
Processes Affected by Predictor=Sediment Only
Hydraulics Update Threshold= 0.02
Energy Slope Method= 1
Volume Change Method= 1
Sediment Retention Method= 0
Sediment TS Multiplier= 1
Warm Up Method= 0
XS Weighting Method= 0
Number of US Weighted Cross Sections= 1
Number of DS Weighted Cross Sections= 1
Upstream XS Weight=0
Main XS Weight=1
Downstream XS Weight=0
Number of DS XS's Weighted with US Boundary= 1
Upstream Boundary Weight= 1
Weight of XSs Associated with US Boundary= 0
Number of US XS's Weighted with DS Boundary= 1
Downstream Boundary Weight= 0.5
Weight of XSs Associated with DS Boundary= 0.5
Percentile Method= 0
Sediment Output Level= 3
Mass or Volume Output= 0
Output Increment Type= 1
Profile and TS Output Increment= 1
Transport Output Increment 1
XS Output Flag= 0
XS Output Increment= 10
Read HDF5 Sediment Hotstart= 0
Sediment Hotstart Type= 0
Write Gradation File= 0
Read Gradation Hotstart= 0
Write HDF5 File= 1
Write Binary Output= 1
Write DSS Sediment File= 0
DSS Sediment Output Type= 1
SV Curve= 0
Specific Gage Flag= 0
Subcell Erosion Methods= 0
Subcell Deposition Methods= 0
Advection Scheme= 1
Matrix Solver= 0
Implicit Weighting Factor= 1
Maximum Outer Loop Convergence Iterations= 5
Convergence Maximum Absolute= 0.001
Convergence RMSE= 0.0001
Grain Fractions Max Abs Error= 0.001
Max Subgrid Regions= 1
Max Subgrid Length Scale= 3.402823E+38
Initial Layer Thickness= 3
Min Layer Thickness= 0.1
Max Layer Thickness= 6
Number of Layers= 5

--- BgTrbbleCk.f01 (steady flow) ---

Flow Title=Flow
Program Version=6.60
Number of Profiles= 1
Profile Names=P100yr
River Rch & RM=BgTrbbleCk,Main            ,16132
     749
River Rch & RM=BgTrbbleCk,Main            ,13169
    1230
River Rch & RM=BgTrbbleCk,Main            ,12567
    1390
River Rch & RM=BgTrbbleCk,Main            ,5700
    1550
Boundary for River Rch & Prof#=BgTrbbleCk,Main            , 1
Up Type= 0
Dn Type= 3
Dn Slope=0.017446
DSS Import GetInterval= 0
DSS Import GetPeak= 0
DSS Import FillOption= 0

--- BgTrbbleCk.g01 (geometry) ---

Geom Title=Geometry
Program Version=6.60

River Reach=BgTrbbleCk      ,Main
Reach XY= 30
      1619053.13       484671.38     1619131.702      483493.165
     1619029.755      483073.201     1619254.604      482065.518
     1619158.208      481370.371     1618624.823       480752.31
     1618319.027       480601.131617916.44811709479795.078045652
1617673.97842584479631.140037308 1617723.0100182479299.182740673
     1617578.976      479104.949     1616749.225      478962.015
     1616631.992      478677.017     1616349.101       478671.29
     1616283.819      478784.676      1616044.45      478548.743
     1615886.398      478606.0081615174.52431483478437.937907187
      1614931.96      478058.7151614696.99023338478080.705784723
     1614309.535      478422.211     1614054.117       478865.84
      1613567.97      479150.564     1613250.085      479621.287
     1613057.843       479501.01      1612815.37      479583.036
     1612362.937      479408.795     1611590.051      479398.323
     1610833.834      479670.411     1609839.771      480278.351

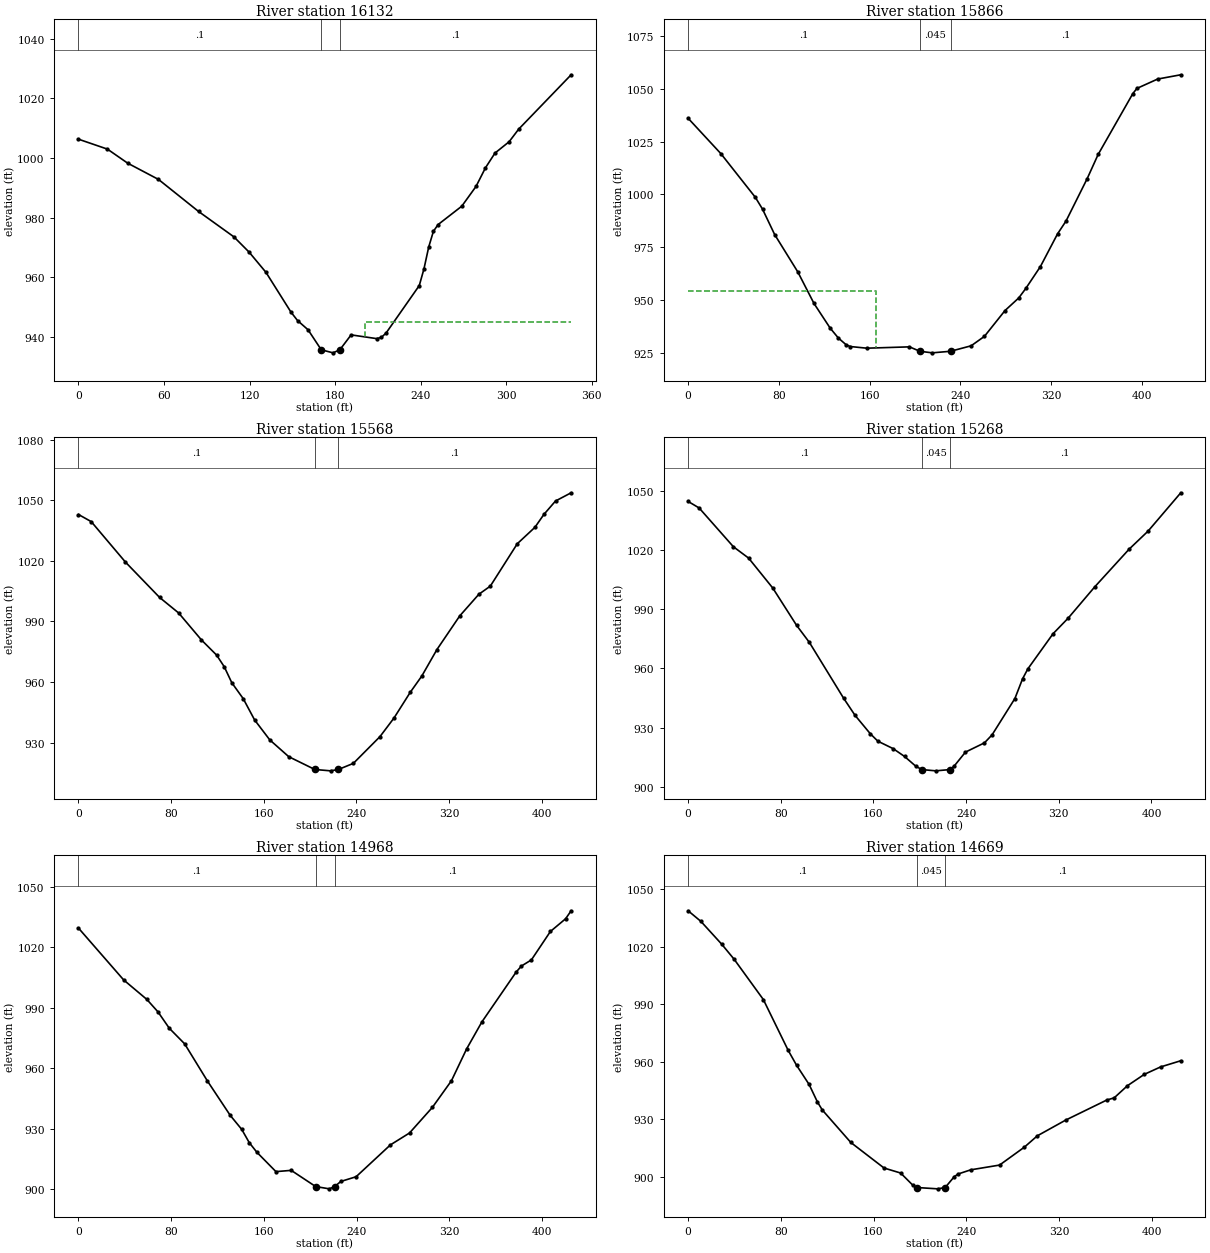
Type RM Length L Ch R = 1 ,16132   ,278.2,266.3,255.1
XS GIS Cut Line= 4
1619145.34310373484809.2846162711619086.68926242484667.373679232
1619054.76074689484639.7281955961618906.79625025484662.360131748
#Sta/Elev= 30
       0 1006.26    20.3 1002.93    34.5  998.22    56.1  992.77    84.2  982.03
     109  973.51   119.7  968.37   131.5   961.6     149  948.29   153.6  945.46
     161  942.35  170.26935.6444   178.5  934.62   183.3935.6467   191.2  940.64
   209.1  939.39   212.4   939.8   215.7  941.25     239  957.18   242.3  962.81
   245.6  970.08   248.9  975.36   252.2  977.63   268.8  983.79   278.8  990.42
   285.4  996.65   292.1 1001.61     302  1005.4   308.7 1009.62   345.5 1027.86
#Mann= 3 ,-1,0
       0      .1       0  170.26    .045       0   183.3      .1       0
#XS Ineff= 2 , 0
                          200.79           944.8
Permanent Ineff=
       F       F
Bank Sta=170.26,183.3
XS Rating Curve= 0 ,0
Exp/Cntr=0.3,0.1

Type RM Length L Ch R = 1 ,15866   ,285.2,297.4,301.8
XS GIS Cut Line= 6
1619246.75776559484328.6461417531619155.83537526484351.791436672
1619084.34896967484382.6758893431618999.93706501 484436.54881309
1618934.68522701484473.5244609271618856.00985943484512.165459752
#Sta/Elev= 30
       0 1036.02    28.9 1019.28    59.3  998.62    65.6  993.06    76.3  981.04
    96.7  963.38     111  948.44   125.3  936.75   132.5  932.08   139.6  928.79
   143.2  928.06   157.5  927.28   195.2  927.91  204.41925.8181   215.3  925.08
   231.4925.8176   249.6  928.41   261.3  932.86   279.5   945.1   291.6  951.05
   297.8  955.53   310.7  965.89   325.8  981.34   333.3  987.43     352 1007.53
   361.6  1018.9   392.2 1047.69   395.8 1050.15   414.1 1054.58   434.5  1056.6
#Mann= 3 ,-1,0
       0      .1       0  204.41    .045       0   231.4      .1       0
#XS Ineff= 2 , 0
          166.11  954.26
Permanent Ineff=
       F       F
Bank Sta=204.41,231.4
XS Rating Curve= 0 ,0
Exp/Cntr(USF)=0,0
Exp/Cntr=0.3,0.1

Type RM Length L Ch R = 1 ,15568   ,300,300,299
XS GIS Cut Line= 6
 1619285.5801945484127.1741037521619198.08168185484126.382110596
1619123.08183184484126.1954311731619023.08203185484125.947400168
1618948.10317917484123.185922757 1618860.8707421484111.894606754
#Sta/Elev= 30
       0 1042.93      11 1039.41    40.6 1019.34    70.1 1001.83    86.5  994.17
   106.2   980.8   119.3   973.3   125.9  967.53   132.4  959.63   142.3  951.71
   152.1   941.2   165.2  931.32   181.6  922.99  204.11916.6577   217.7  915.98
  224.49916.6581   237.4  919.68   260.4  932.93   272.5  942.14   286.6  954.92
   296.5  962.91   309.6  976.06   329.3  992.72   345.8 1003.43   355.7 1007.46
     379 1028.46   394.2 1036.57     402 1042.99     412 1049.61   425.5 1053.69
#Mann= 3 ,-1,0
       0      .1       0  204.11    .045       0  224.49      .1       0
Bank Sta=204.11,224.49
XS Rating Curve= 0 ,0
Exp/Cntr(USF)=0,0
Exp/Cntr=0.3,0.1

Type RM Length L Ch R = 1 ,15268   ,297.2,300,302.1
XS GIS Cut Line= 6
1619270.94636551483825.6199168411619183.13879834483823.557913095
 1619108.2340925483827.3380892571619008.36126076483832.381714344
1618933.45688301483836.1641870891618846.06827825483840.577236012
#Sta/Elev= 30
       0 1044.65     9.5 1041.34    39.1 1021.67    52.2 1015.94    73.1 1000.73
    93.7  981.79   104.7  973.18   134.2  944.94   144.1  936.23   157.3  926.89
   163.8  923.14     177  919.36   186.8  915.41   196.7  910.37  201.87908.7386
   213.8  908.11   225.9908.7394   229.5   910.4   239.4   917.6   255.8  922.29
   262.4  926.35   282.1  944.77   288.7  954.73   293.3  959.81     315  977.58
   328.1  985.51   351.1 1001.41   380.7 1020.46   397.1 1029.63   425.3 1049.04
#Mann= 3 ,-1,0
       0      .1       0  201.87    .045       0   225.9      .1       0
Bank Sta=201.87,225.9
XS Rating Curve= 0 ,0
Exp/Cntr(USF)=0,0
Exp/Cntr=0.3,0.1

Type RM Length L Ch R = 1 ,14968   ,304.3,299.9,295.2
XS GIS Cut Line= 6
1619339.80482359483555.4475569281619252.25611417483552.457405418
1619177.34287818483548.3258520071619077.67805126483540.145750254
 1619002.9295131483534.0112480821618915.45724709483530.120835915
#Sta/Elev= 30
       0 1029.44      39 1003.73      59  994.07    68.6   987.9    78.4  979.75
    91.6  972.06   111.3   953.6     131  936.54   140.9  929.61   147.4  923.03
     154  918.25   170.4  908.67   183.6  909.29  204.73901.2595   216.5  900.13
   221.1901.2571   226.4  903.79   239.6  906.13   269.2  921.92   285.7  927.82
   305.4   940.5   321.9  953.74     335  969.53   348.2  982.94   377.7  1007.6
   382.3 1010.63   390.9 1013.67   407.3 1027.76   420.4 1034.06   425.2 1038.03
#Mann= 3 ,-1,0
       0      .1       0  204.73    .045       0   221.1      .1       0
Bank Sta=204.73,221.1
XS Rating Curve= 0 ,0
Exp/Cntr(USF)=0,0
Exp/Cntr=0.3,0.1

Type RM Length L Ch R = 1 ,14669   ,290.1,300.1,304.1
XS GIS Cut Line= 6
  1619251.731837483171.0887455941619171.76677383483206.903962672
1619103.30201575483237.659150511 1619011.2067275483276.627248421
1618942.08350617483305.8125575041618861.39534734483339.763277009
#Sta/Elev= 30
       0 1038.63      11 1033.12      29 1021.21    39.7 1013.38    64.9   992.4
    86.4  965.86    93.6  958.14   104.4  948.17   111.6  939.02   115.8  934.86
   140.4  917.94   169.1  904.62   183.4  902.02     194  895.63  197.48894.4689
   215.4  893.78  221.86894.4683   229.7  900.13   233.2  901.55   243.9  903.68
   268.8  906.16   290.2  915.49   301.4   921.4   325.8  929.57   361.4  940.06
   367.7  941.17   379.2  947.52   393.7  953.41   407.7  957.27   425.2  960.51
#Mann= 3 ,-1,0
       0      .1       0  197.48    .045       0  221.86      .1       0
Bank Sta=197.48,221.86
XS Rating Curve= 0 ,0
Exp/Cntr(USF)=0,0
Exp/Cntr=0.3,0.1

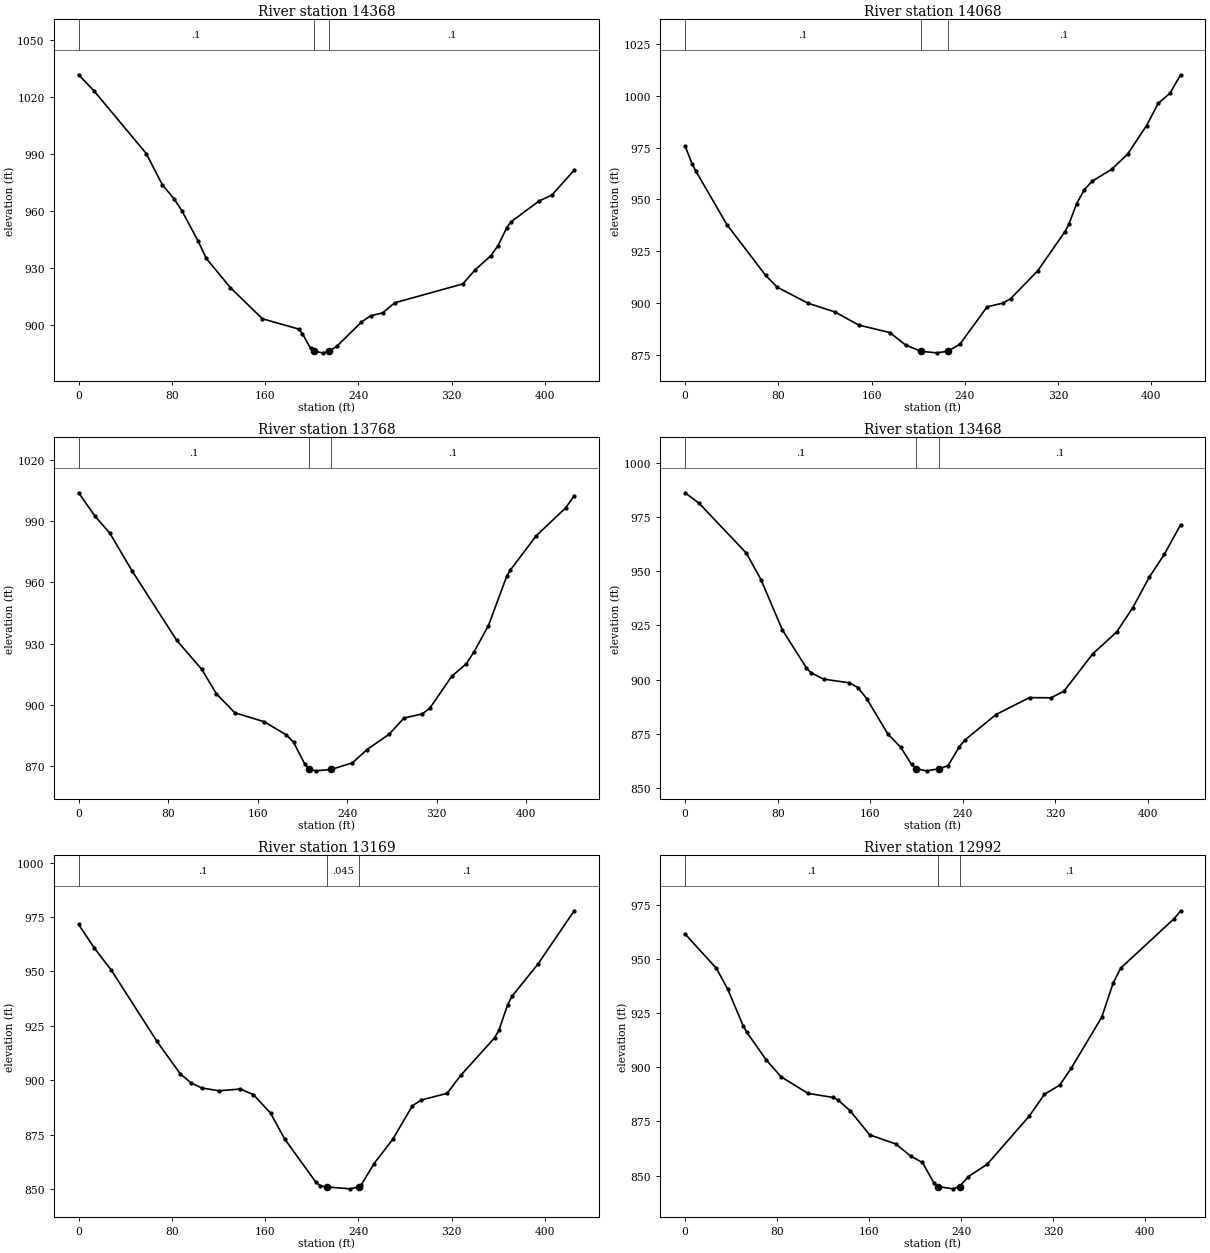
Type RM Length L Ch R = 1 ,14368   ,304.8,300,294.9
XS GIS Cut Line= 6
1619251.11930542483027.7625886651619167.60175592483001.665199921
1619096.01594108482979.2938535961619000.56796926482949.466813505
1618928.98182634482927.0957952591618845.49380434482900.904246584
#Sta/Elev= 30
       0 1031.68    13.3 1023.11      58  990.16    71.7  973.79      82  966.19
    88.9  959.62   102.6  943.87   109.5  934.87   130.1  919.51   157.6  903.08
   188.6  897.68     192  895.12   198.9  887.53  201.66885.9849   209.2  885.12
  215.08885.9871   221.5  888.63   242.4  901.27   250.4  904.66   260.7  906.19
   271.2  911.52   329.5  921.45   339.8   928.7   353.6  936.35   359.6  941.53
   367.3  951.18   370.8  954.15   394.8  965.11   405.9  968.29     425   981.4
#Mann= 3 ,-1,0
       0      .1       0  201.66    .045       0  215.08      .1       0
Bank Sta=201.66,215.08
XS Rating Curve= 0 ,0
Exp/Cntr(USF)=0,0
Exp/Cntr=0.3,0.1

Type RM Length L Ch R = 1 ,14068   ,296.2,300.3,301.7
XS GIS Cut Line= 6
1619306.77044085 482641.561589421619220.15447234482654.368650422
1619146.40855683482668.0257753431619048.08001333482686.234728426
1618974.33409785482699.8918533331618888.29686834  482715.8255485
#Sta/Elev= 30
       0  975.79       6  967.09     9.4  963.43    35.9  937.76    69.1  913.26
      79  907.57   105.6   899.8   128.5  895.64     149  889.29   175.7  885.64
   189.1  879.68   202.2876.6503   215.7  875.88  225.44876.6493   235.8  880.11
   259.1   898.1   272.5  899.86   279.2  901.99   302.5  915.47   325.9  934.44
   329.2  937.94   335.9  947.93   342.5  954.65   349.2  958.74   365.9  964.49
   379.6   971.8   395.9  985.63   405.9  996.34     416 1001.24   425.1 1010.12
#Mann= 3 ,-1,0
       0      .1       0   202.2    .045       0  225.44      .1       0
Bank Sta=202.2,225.44
XS Rating Curve= 0 ,0
Exp/Cntr(USF)=0,0
Exp/Cntr=0.3,0.1

Type RM Length L Ch R = 1 ,13768   ,293.9,299.7,302.7
XS GIS Cut Line= 6
  1619377.881191482405.0105533451619290.42893809482402.120139167
1619215.46977042482399.6424538341619113.87220459482395.591937006
1619031.16994217 482390.928560511618935.61173435482386.205144763
#Sta/Elev= 30
       0 1003.91    14.8  992.32    27.9  984.15    47.6   965.8    87.5  931.79
     110  917.47   123.1  905.52   139.5  896.22   165.8  891.85   185.5  885.41
     192  881.81   201.9  871.28  205.75868.5042   211.7  867.81  225.63868.5044
   244.6  871.71   257.7  878.25   277.4  885.74   290.6  893.62     307  895.69
   313.6  898.37   333.3  914.08   346.4  920.26     353  925.84   366.1   938.9
   382.5  963.13   385.8  966.19   408.8  982.85   435.1  996.52   442.7 1002.47
#Mann= 3 ,-1,0
       0      .1       0  205.75    .045       0  225.63      .1       0
Bank Sta=205.75,225.63
XS Rating Curve= 0 ,0
Exp/Cntr(USF)=0,0
Exp/Cntr=0.3,0.1

Type RM Length L Ch R = 1 ,13468   ,310.4,299.8,289.6
XS GIS Cut Line= 6
1619409.94051009482235.8297893411619332.51021875482195.076590002
  1619266.141257482160.1458855871619177.64930801 482113.57117559
1619111.28067434482078.6398150031619025.42028175482049.498797178
#Sta/Elev= 30
       0  986.06    12.1  981.22    52.9   958.3    65.6  946.05      84  922.95
   104.8  905.47   108.5   903.3   119.6  900.26   141.9  898.55   149.3  896.37
   156.9  891.29   175.2  874.99   186.4  868.82   195.7  860.96  199.72 858.952
   208.6  858.03   219.4  858.95   227.2  860.41     237  869.14     242  872.32
   268.6  883.94   297.6  891.75   316.1  891.66   327.3  894.67   352.2  911.87
     373  922.01   386.8  933.13   401.2  947.31   414.2   957.8   428.2  971.39
#Mann= 3 ,-1,0
       0      .1       0  199.72    .045       0   219.4      .1       0
Bank Sta=199.72,219.4
XS Rating Curve= 0 ,0
Exp/Cntr(USF)=0,0
Exp/Cntr=0.3,0.1

Type RM Length L Ch R = 1 ,13169   ,173.3,176.6,181.7
XS GIS Cut Line= 6
1619381.51897901481759.2054145041619303.75141801 481799.31097734
1619237.09341484481833.687220916  1619148.216296481879.521774918
1619081.55829284481913.8980185091619004.26481226481954.922542751
#Sta/Elev= 30
       0  971.53    13.6  960.59    28.1  950.51    67.1  917.89    87.1  902.95
    96.4  898.75   105.6  896.42   120.4  895.13   138.8  895.93   149.9  893.35
   164.6  884.86   176.7     873   203.5  853.11   207.3  851.45  213.25850.9236
   232.7  850.07  240.16850.9226   242.2  851.69   253.3  861.63   269.3  872.75
   286.3  888.22   293.6  890.83     316  893.95   327.7   902.2   356.7  919.42
   360.4   922.9   367.9  934.56   371.6  938.49   393.9  953.32     425  977.83
#Mann= 3 ,-1,0
       0      .1       0  213.25    .045       0  240.16      .1       0
Bank Sta=213.25,240.16
XS Rating Curve= 0 ,0
Exp/Cntr(USF)=0,0
Exp/Cntr=0.3,0.1

Type RM Length L Ch R = 1 ,12992   ,231.9,233.8,234
XS GIS Cut Line= 2
1619370.32310252481659.9891366221618944.17114162481721.725436793
#Sta/Elev= 30
       0  961.54    27.2  945.68    37.1     936    50.4  919.28    53.7  916.12
    70.6  903.33    83.5  895.59   106.7     888   128.6  886.07   133.2  884.79
   143.2  880.05   160.4  868.83     183  864.64   196.2  858.96   206.2  856.07
   216.1  846.82  219.89844.9662   232.6  843.91   238.6  844.98     246  849.51
   262.5  855.25     299  877.46   312.3  887.56   325.5  891.77   335.5  899.58
     362  923.06   371.9  938.81   378.6  945.82     425  968.64   430.6  972.25
#Mann= 3 ,-1,0
       0      .1       0  219.89    .045       0   238.6      .1       0
Bank Sta=219.89,238.6
XS Rating Curve= 0 ,0
Exp/Cntr(USF)=0,0
Exp/Cntr=0.3,0.1

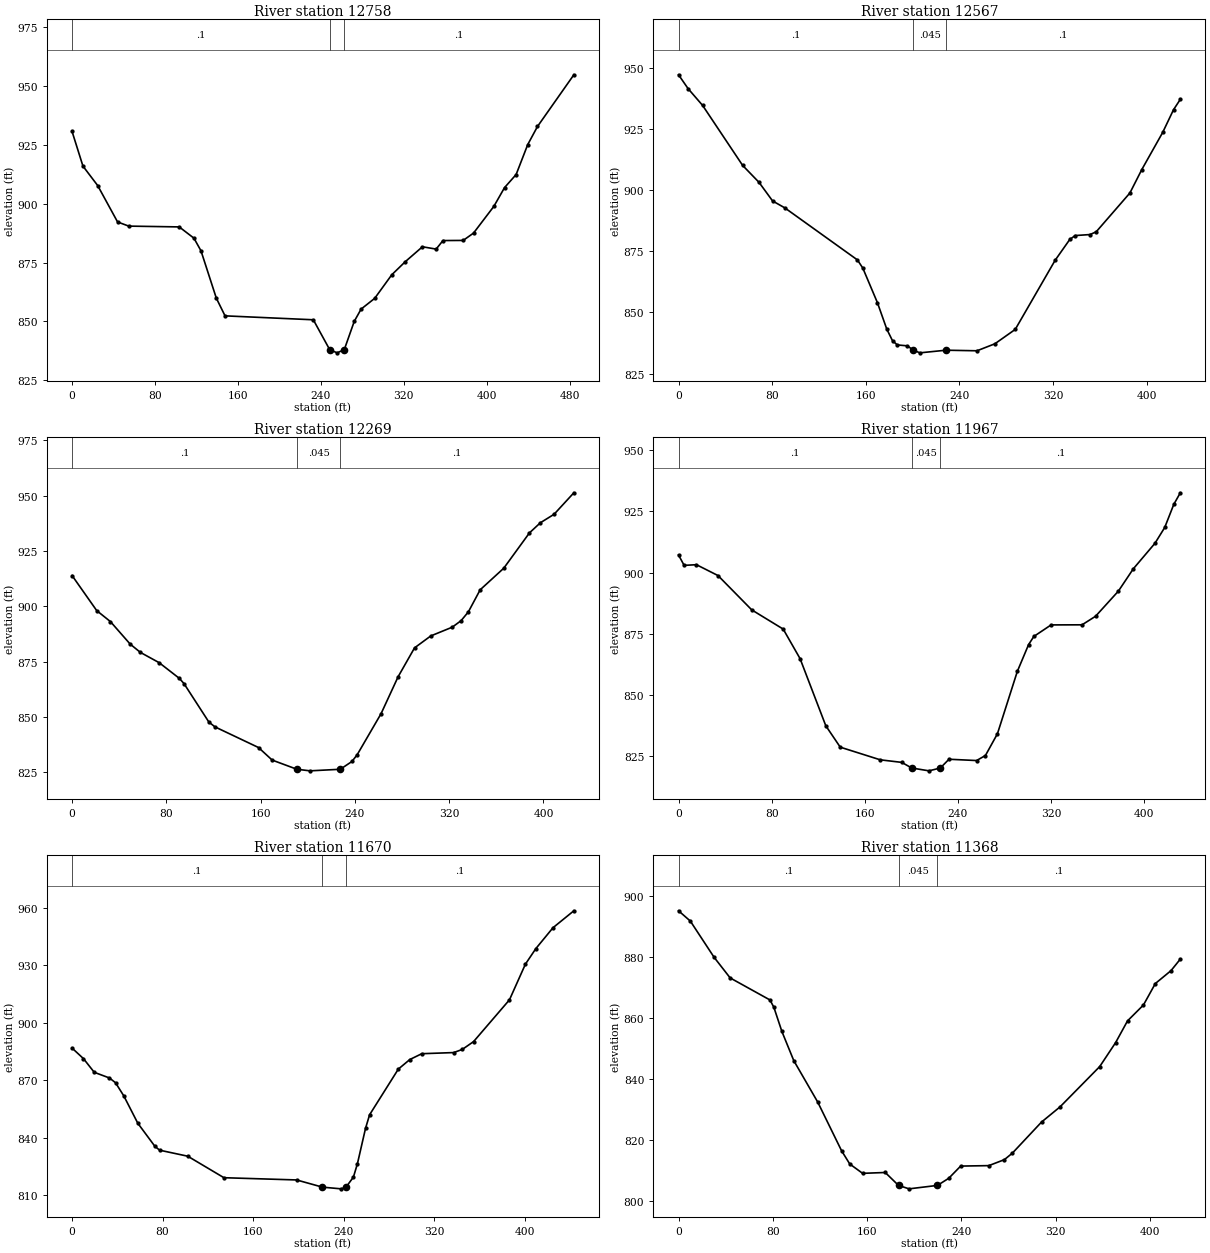
Type RM Length L Ch R = 1 ,12758   ,197.1,190.7,180.7
XS GIS Cut Line= 4
1619368.39236484481598.055474341  1619212.091632  481458.0231789
1619053.99592018481471.0123499681618947.86564684481517.162273629
#Sta/Elev= 30
       0  930.76    10.5  916.04    24.7  907.79    43.9  892.31    54.7  890.54
   103.4   890.2   117.6  885.41   124.4  880.04   139.2  859.92   147.6   852.4
   232.8  850.73   248.6  838.03   255.8  836.68  262.69838.0667   272.3  850.07
   278.9  855.27     292  859.83   308.5  869.86   321.6  875.45   338.1  881.76
   351.3  880.77   357.9   884.4   377.4  884.46   387.4  887.58     407  898.93
   417.3   906.9   428.5  912.47   439.7   925.2   449.1  932.88   484.2  954.86
#Mann= 3 ,-1,0
       0      .1       0   248.6    .045       0  262.69      .1       0
Bank Sta=248.6,262.69
XS Rating Curve= 0 ,0
Exp/Cntr(USF)=0,0
Exp/Cntr=0.3,0.1

Type RM Length L Ch R = 1 ,12567   ,294.5,298,299.5
XS GIS Cut Line= 6
1619221.08918175481142.8838125021619165.11783701 481210.14056775
1619117.14253926 481267.789074511619053.17481942481344.653750166
 1619005.4429595481402.5046843441618933.84992684481459.308704585
#Sta/Elev= 30
       0  947.17     8.2  941.49    20.6  934.63    54.8  910.12    68.8   903.2
    80.4  895.59    90.8  892.78   152.9  871.49   157.5  868.16     170  854.01
     178   843.2   182.9  838.45     187  836.74   195.6  836.37  200.68834.5883
   206.3  833.51  228.62834.5879   255.1  834.35   270.4  837.21   287.8  843.09
   321.9  871.35   334.4  879.85     339  881.45   351.7  881.86     357  882.99
   385.8  898.85     396  908.45   413.8  923.58   423.1   932.9   428.9  937.13
#Mann= 3 ,-1,0
       0      .1       0  200.68    .045       0  228.62      .1       0
Bank Sta=200.68,228.62
XS Rating Curve= 0 ,0
Exp/Cntr(USF)=0,0
Exp/Cntr=0.3,0.1

Type RM Length L Ch R = 1 ,12269   ,297.6,302,304.7
XS GIS Cut Line= 6
1619034.35956834480971.8405194281618965.36134675481026.334833011
1618906.44282943481073.2750278411618831.66738842 481139.78998667
1618777.64321826481191.8131765871618714.61512908481252.506624758
#Sta/Elev= 30
       0  913.92    20.9  898.09    32.6  893.09    49.3  882.95      58  879.19
    73.9  874.55    91.1  867.44      95  865.09   116.1  847.72   121.3  845.54
   158.2  836.22   169.8  830.55   190.8   826.4   201.9  825.69   227.6   826.4
   237.5  829.92   241.9  832.93   262.2  851.51   276.7  868.23   290.6  881.24
   304.4  886.64   322.6  890.59   330.1  893.53   336.3  897.52   346.3  907.48
   366.3  917.22   388.1  933.18   397.4  937.77     409  941.59   425.8  951.31
#Mann= 3 ,-1,0
       0      .1       0   190.8    .045       0   227.6      .1       0
Bank Sta=190.8,227.6
XS Rating Curve= 0 ,0
Exp/Cntr(USF)=0,0
Exp/Cntr=0.3,0.1

Type RM Length L Ch R = 1 ,11967   ,305.3,298,287.9
XS GIS Cut Line= 6
1618874.77327333480775.4258860051618796.20453285480817.502245426
1618728.47172867480849.7114985881618638.41613451480893.185821086
1618571.85393168480927.8199381681618507.23463833480993.068167254
#Sta/Elev= 30
       0  907.17     4.8  902.93    15.4   903.2    33.9  898.76    62.9  884.72
    89.9  876.87   104.4  864.78   126.5  837.33   138.9  828.59   173.3  823.41
   191.7  822.37   200.3  820.07   215.1  818.91  224.86  820.07   232.3  823.65
     256  823.12   263.6  825.18   273.9  834.06     291  859.58   300.7  870.56
   305.2  873.87     320  878.58   346.6  878.62   358.2  882.12   377.8   892.4
   390.6  901.51   409.2  911.95   417.6  918.42   425.4  927.88     431  932.61
#Mann= 3 ,-1,0
       0      .1       0   200.3    .045       0  224.86      .1       0
Bank Sta=200.3,224.86
XS Rating Curve= 0 ,0
Exp/Cntr(USF)=0,0
Exp/Cntr=0.3,0.1

Type RM Length L Ch R = 1 ,11670   ,287.7,301.4,311.7
XS GIS Cut Line= 6
1618553.57739343480542.4151971791618516.65391085 480633.21652475
1618485.06211051480708.3715581741618444.29480359480801.190926343
1618416.96480575480871.0342905821618385.08002701480952.518051505
#Sta/Elev= 30
       0  886.79    10.1  881.26    19.6  874.14      33  871.19    38.4   868.7
    45.7  861.84    58.1  847.54    73.2   835.5    77.4  833.48   102.2  830.35
   134.2  819.12   198.4  817.95  221.26814.1905   237.8  813.31  242.05814.1896
   248.6  819.43   252.1   826.3   259.3  844.86   262.9  851.97   288.3  875.82
   298.4  880.79     309  883.85   337.2  884.44   344.8  886.08   354.8  890.18
   386.5  911.98   400.6  930.61   409.8  938.71     425  949.63   443.4  958.46
#Mann= 3 ,-1,0
       0      .1       0  221.26    .045       0  242.05      .1       0
Bank Sta=221.26,242.05
XS Rating Curve= 0 ,0
Exp/Cntr(USF)=0,0
Exp/Cntr=0.3,0.1

Type RM Length L Ch R = 1 ,11368   ,297.9,290.1,281.6
XS GIS Cut Line= 6
1618500.10079435480467.8572754261618414.44053259480489.096734256
1618341.45937935480506.3821327541618244.15150309480529.428674594
1618171.17067793480546.713745013 1618086.0258351480566.879387096
#Sta/Elev= 30
       0  895.27      10   891.9    30.2  880.01    43.8  873.26    77.6  866.03
    80.9  863.63    87.7  855.71    97.8  846.14   118.1  832.57   138.3  816.64
   145.3  812.26   156.2   809.2   175.4  809.48  186.66805.2475   195.6  804.12
   219.7805.2458   229.3  807.58   239.4  811.58   263.3  811.73   276.5  813.69
   283.3  815.83     308     826   323.7  830.98   357.4   844.2   370.9  852.06
     381  859.18   394.5  864.38   404.6  871.42   417.9  875.65   425.8  879.43
#Mann= 3 ,-1,0
       0      .1       0  186.66    .045       0   219.7      .1       0
Bank Sta=186.66,219.7
XS Rating Curve= 0 ,0
Exp/Cntr(USF)=0,0
Exp/Cntr=0.3,0.1

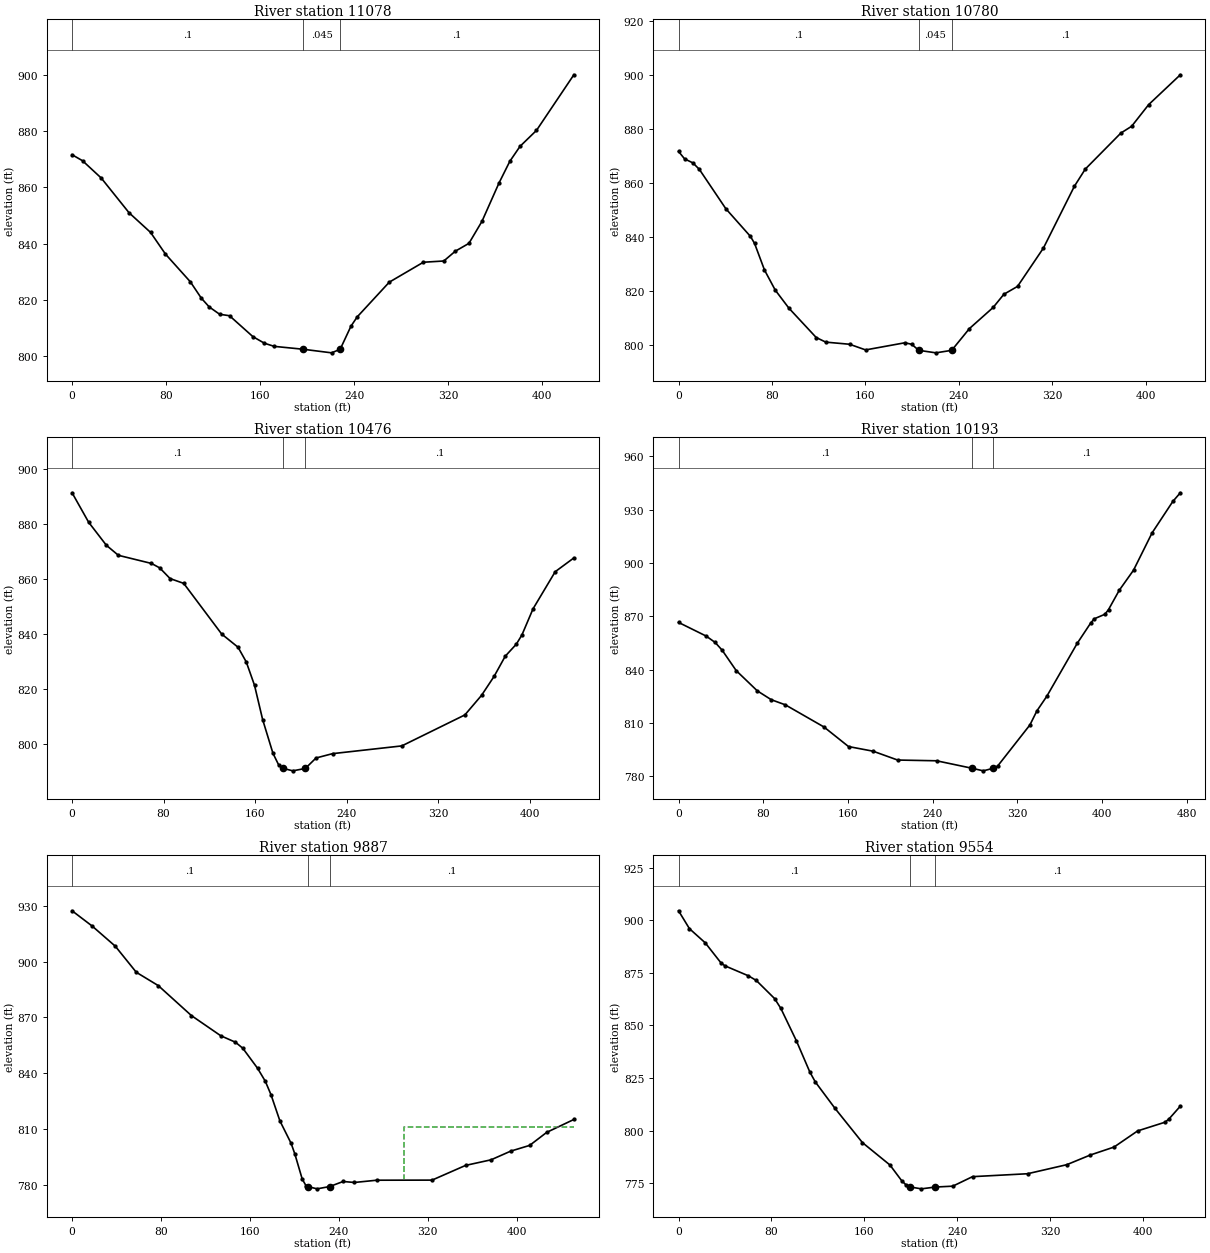
Type RM Length L Ch R = 1 ,11078   ,296.3,298.1,296.5
XS GIS Cut Line= 6
1618320.67136317480150.1751680081618246.99926643480200.000527665
1618187.54630134480246.6136234251618113.67472993480314.163685173
1618060.64137143480367.196059421  1617998.769776480429.068311006
#Sta/Elev= 30
       0  871.59     8.9  869.46    24.8  863.33    48.5     851    66.8  844.03
    79.5  836.33   100.7  826.48     110   820.7   116.7  817.59   125.6  814.98
     134  814.46   153.9  807.04   163.7   804.7     172  803.59  196.52 802.572
   220.9  801.29  228.22802.5717   237.4  810.76   242.7  814.05     270  826.37
     299  833.44   316.4  833.88   326.2  837.36   337.8  840.14   348.9  847.96
   363.4  861.57   372.6  869.26   381.3  874.57   395.3  880.23   427.1  899.96
#Mann= 3 ,-1,0
       0      .1       0  196.52    .045       0  228.22      .1       0
Bank Sta=196.52,228.22
XS Rating Curve= 0 ,0
Exp/Cntr(USF)=0,0
Exp/Cntr=0.3,0.1

Type RM Length L Ch R = 1 ,10780   ,306.4,304.4,302.9
XS GIS Cut Line= 6
1618162.52797867 479901.554602251618089.41821675479954.652921259
1618027.82778876480000.0537490841617954.65306634480068.703218088
 1617904.3349255480124.3189205081617845.62999043 480189.20330517
#Sta/Elev= 30
       0  871.62     5.2  868.86    12.3  867.37    17.8     865    40.5  850.44
    61.6  840.19    65.1  837.62    73.6  827.78    82.8  820.36    94.5  813.68
   117.9  802.82   126.1  801.12   146.5  800.33   160.2  798.24   193.8  800.88
   199.7  800.32  205.71798.0869   220.4  797.16  233.92798.0867   249.1  806.13
   269.4  813.93   278.6  818.81   290.3  821.72   312.5  835.92     339  858.75
   348.3  865.08   378.8  878.41     388  880.91   402.6  888.92   429.7  899.95
#Mann= 3 ,-1,0
       0      .1       0  205.71    .045       0  233.92      .1       0
Bank Sta=205.71,233.92
XS Rating Curve= 0 ,0
Exp/Cntr(USF)=0,0
Exp/Cntr=0.3,0.1

Type RM Length L Ch R = 1 ,10476   ,272.6,282.3,290.1
XS GIS Cut Line= 4
1618013.83312937479638.6565745441617903.31491442479708.656366006
1617848.97751286 479831.007606861617731.41250817479959.235358955
#Sta/Elev= 30
       0  891.43    14.5  880.72      30  872.35    40.5  868.71    69.4  865.76
    76.6  864.15    85.7  860.26    97.6  858.52   130.8  840.11   145.1  835.32
   152.3  829.97   159.5   821.5   166.6  809.05   175.6  796.82   180.6  792.57
  184.69791.2829     193  790.41  203.94791.2831   213.3  795.08   227.8  796.66
   288.3  799.47   343.4  810.72     358  817.84     369  824.75   378.7  832.05
   388.4  836.43   393.3  839.78     403  849.26   422.4  862.76   438.7  867.76
#Mann= 3 ,-1,0
       0      .1       0  184.69    .045       0  203.94      .1       0
Bank Sta=184.69,203.94
XS Rating Curve= 0 ,0
Exp/Cntr(USF)=0,0
Exp/Cntr=0.3,0.1

Type RM Length L Ch R = 1 ,10193   ,304.5,305.9,305.7
XS GIS Cut Line= 4
1617943.93243729 479552.424102151617716.78518731479585.947923018
1617616.54562384479612.2916184191617479.65029958479645.277859156
#Sta/Elev= 30
       0   866.6    26.1  858.92    34.6  855.33    41.2     851    54.5   839.5
    74.4  828.14    87.6  823.16   100.9  820.28   137.4  807.83   160.6  796.83
   183.8  794.22     207  789.25   243.8  788.83  277.36 784.625   287.9  783.18
  297.42784.6254   301.5  785.87     332  808.98   338.6  816.89   347.9  825.04
   376.7  854.85   389.4  866.24   392.8  868.63   402.9  871.19   406.3  873.85
   416.4  884.66   429.9  895.96   447.4   916.9     467  934.57   474.1  939.45
#Mann= 3 ,-1,0
       0      .1       0  277.36    .045       0  297.42      .1       0
Bank Sta=277.36,297.42
XS Rating Curve= 0 ,0
Exp/Cntr(USF)=0,0
Exp/Cntr=0.3,0.1

Type RM Length L Ch R = 1 ,9887    ,347.5,332.9,324.9
XS GIS Cut Line= 6
 1617944.0832056479279.6024340841617857.25890417 479290.45575884
1617782.83812125 479299.758561761617684.55354093479319.708981171
1617607.05238359479333.1715526731617500.41512968479360.269267499
#Sta/Elev= 30
       0  927.48    18.1  919.24    38.9  908.39    57.8  894.34    77.6  887.15
   107.4  871.01   133.8  860.14     147  856.66   153.6  853.43   166.9  842.64
   173.9   835.6     179  828.37     187  814.28   197.1  802.17   200.4  796.55
   207.1  782.91   210.4  779.45  211.94 778.904   220.5  777.67  231.77778.9033
   243.9  781.63     254   781.1   274.2  782.32   323.9  782.37   354.1   790.3
     377  793.31   394.7  797.99   411.7  801.07   427.1  808.11   451.5  815.04
#Mann= 3 ,-1,0
       0      .1       0  211.94    .045       0  231.77      .1       0
#XS Ineff= 2 , 0
                          298.45          810.74
Permanent Ineff=
       F       F
Bank Sta=211.94,231.77
XS Rating Curve= 0 ,0
Exp/Cntr(USF)=0,0
Exp/Cntr=0.3,0.1

Type RM Length L Ch R = 1 ,9554    ,260.2,267.8,268.8
XS GIS Cut Line= 2
1617564.82904284478885.8181166651617458.16980734479304.600415587
#Sta/Elev= 30
       0  904.54     9.4  896.03      23   889.3    36.5   879.8    39.9  878.38
    60.2  873.61      67  871.39    82.7  862.81    88.1  858.14   101.6   842.6
   113.1  827.85   117.8  823.15   134.7  810.63   158.4  794.29   182.1  783.64
   192.2  776.18     196  774.16   199.5  773.19   209.2  772.31 221.198773.1648
   236.2  773.58   253.2   778.1   300.6  779.49   334.4  783.79   354.7   788.4
   375.1  792.18   395.4  799.85   419.1  804.01   422.7   805.7   432.2  811.63
#Mann= 3 ,-1,0
       0      .1       0   199.5    .045       0 221.198      .1       0
Bank Sta=199.5,221.198
XS Rating Curve= 0 ,0
Exp/Cntr(USF)=0,0
Exp/Cntr=0.3,0.1

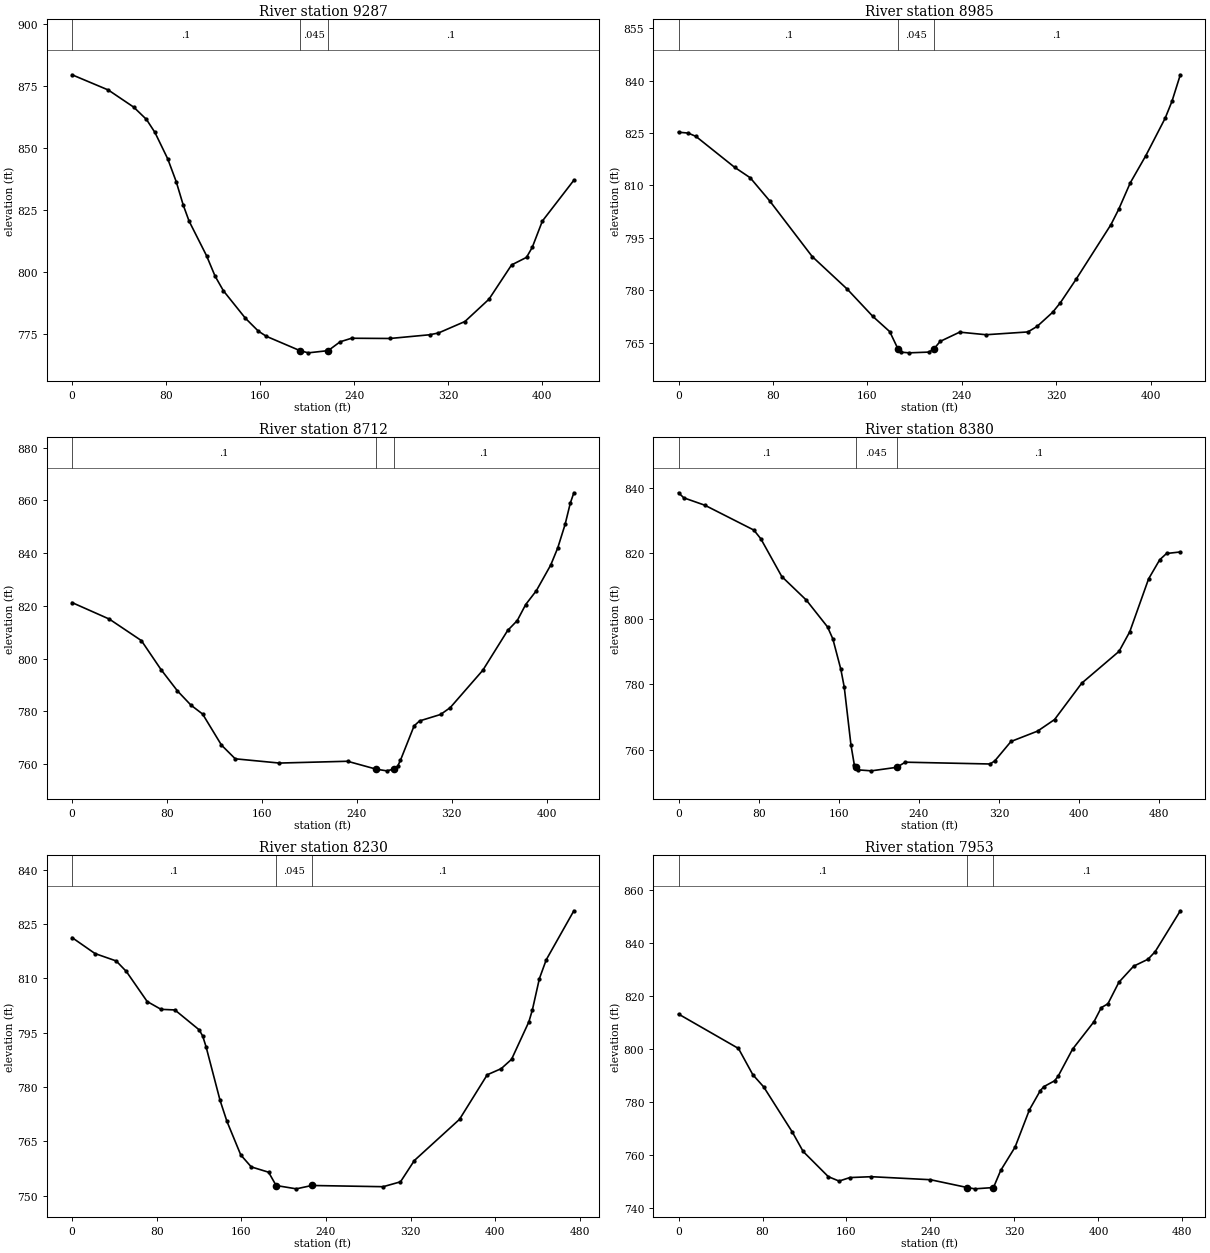
Type RM Length L Ch R = 1 ,9287    ,312.2,301.4,299.1
XS GIS Cut Line= 6
1617357.81567734478827.6115401691617321.03917609478907.439464509
1617286.89127851478974.6470072571617233.32380034479059.248872176
1617196.93017234479125.3429000821617157.92729759479204.378503174
#Sta/Elev= 30
       0  879.41    30.8  873.28    52.5  866.35    63.3  861.41    70.5  856.17
    81.4  845.52    88.6  836.36    94.6  826.88    99.6  820.39   114.4   806.5
   121.7  798.23   128.8  792.32   147.5  781.26   158.5  776.07   165.3  773.98
   193.9   768.2     201  767.31  217.94768.1991   228.1  771.76   237.8  773.19
   270.6   773.1   304.3   774.6   311.8  775.32   334.3  779.94   354.8  788.95
     374  802.75   386.7   805.8   391.6  809.84   400.2  820.44     427   836.9
#Mann= 3 ,-1,0
       0      .1       0   193.9    .045       0  217.94      .1       0
Bank Sta=193.9,217.94
XS Rating Curve= 0 ,0
Exp/Cntr(USF)=0,0
Exp/Cntr=0.3,0.1

Type RM Length L Ch R = 1 ,8985    ,271,273.7,281.6
XS GIS Cut Line= 6
1616978.62549084478742.4804768411616974.18225826478829.867441177
1616970.37419501478904.7708346691616965.29612118479004.641697928
1616961.48772985479079.5447633421616957.04416917479166.932055756
#Sta/Elev= 30
       0  825.26     8.1  825.02    14.7  824.07    47.5  815.21    60.7  812.21
    77.1  805.63   113.2  789.64   142.9  780.29   164.6  772.47   178.9  768.11
  186.02763.0456   188.8  762.22   195.4  762.04   211.8  762.25  215.99 763.043
   221.6  765.32   238.1  767.97   260.5  767.23   295.9  768.03   303.8  769.64
   316.9  773.67   323.5  776.45   336.7  783.12   366.2  798.76   372.8  803.17
   382.6  810.75   395.8  818.56   412.2  829.31   417.9   834.1     425  841.72
#Mann= 3 ,-1,0
       0      .1       0  186.02    .045       0  215.99      .1       0
Bank Sta=186.02,215.99
XS Rating Curve= 0 ,0
Exp/Cntr(USF)=0,0
Exp/Cntr=0.3,0.1

Type RM Length L Ch R = 1 ,8712    ,348.2,331.2,315.5
XS GIS Cut Line= 3
1616895.47245905478745.890714689  1616679.486699478956.829181566
1616609.14412654479055.180672291
#Sta/Elev= 30
       0  821.23    31.4  814.97    58.4  806.82    74.9  795.86    88.8  787.74
   100.2  782.33     110  778.97   125.9  767.19   137.5     762   174.7  760.39
   232.1  761.07   256.1  758.09     265  757.44  271.38758.1073   274.5  759.35
   276.7  761.46   288.2  774.49   292.8  776.36   310.5  778.81   318.6  781.39
   346.1  795.58     367  810.65   375.1  814.41   382.2  820.48   391.2  825.74
   403.3  835.46   409.2  841.93   415.4  850.84   419.8  858.93   422.8  862.86
#Mann= 3 ,-1,0
       0      .1       0   256.1    .045       0  271.38      .1       0
Bank Sta=256.1,271.38
XS Rating Curve= 0 ,0
Exp/Cntr(USF)=0,0
Exp/Cntr=0.3,0.1

Type RM Length L Ch R = 1 ,8380    ,155.7,150.1,145.2
XS GIS Cut Line= 3
1616632.25916651478479.8498377611616581.07936992478620.005656168
1616493.50209709478960.794344018
#Sta/Elev= 30
       0  838.39     5.3  836.84    26.3  834.59    75.2  827.01    82.2  824.34
   103.1  812.83   127.6  805.64   148.8  797.45   154.1  793.79   162.1   784.5
   165.5  779.05   172.2  761.39   175.6  755.24   177.2  754.61     179  753.83
   192.6  753.53  217.96 754.608   226.4  756.17   311.1  755.62   315.8  756.56
     332  762.49   358.6  765.66   375.5  769.18   402.6  780.27   439.9  789.99
   450.6  795.97   469.4  812.11   480.5  817.94   487.3  819.86   501.1  820.33
#Mann= 3 ,-1,0
       0      .1       0   177.2    .045       0  217.96      .1       0
Bank Sta=177.2,217.96
XS Rating Curve= 0 ,0
Exp/Cntr(USF)=0,0
Exp/Cntr=0.3,0.1

Type RM Length L Ch R = 1 ,8230    ,273.7,276.8,272.5
XS GIS Cut Line= 3
1616416.73693828478453.2590620911616420.90088451478808.418009013
1616425.72502184478927.569345504
#Sta/Elev= 30
       0  821.22    21.7  816.81    41.7  814.77    51.3  811.87      71  803.57
    84.1  801.41    97.2  801.24   120.2  795.74   123.5  794.03   126.7  791.06
   139.9  776.29   146.4  770.49   159.5   761.2   169.4  757.91   185.8  756.44
  192.91752.7705     212  751.85   226.7752.7759   294.1  752.44   310.5  753.79
   323.6  759.67   366.3  771.04   392.5  783.34   405.7  785.03   415.5  787.61
   431.9  797.99   435.2  801.28   441.8  809.88   448.3   815.1   474.4  828.62
#Mann= 3 ,-1,0
       0      .1       0  192.91    .045       0   226.7      .1       0
Bank Sta=192.91,226.7
XS Rating Curve= 0 ,0
Exp/Cntr(USF)=0,0
Exp/Cntr=0.3,0.1

Type RM Length L Ch R = 1 ,7953    ,163.4,168.9,171.7
XS GIS Cut Line= 2
1616319.12738316478475.9684796331616183.62933066478934.332985373
#Sta/Elev= 30
       0  813.01    57.1  800.03    70.8  790.11    81.1  785.54   108.5  768.42
   118.7  761.17   142.7  751.66   152.9     750   163.2  751.32   183.7  751.65
     240  750.51  275.08747.5613   282.2  747.07     300  747.56   306.9  754.02
   320.6  762.83   334.3  776.93   344.5  784.04   347.9  785.61   358.2  787.83
   361.6  789.56   375.3  799.74   395.8  810.16   402.7  815.44     409  816.88
   419.5  825.03   433.5  831.07   447.2  833.69     454  836.53     478  851.98
#Mann= 3 ,-1,0
       0      .1       0  275.08    .045       0     300      .1       0
Bank Sta=275.08,300
XS Rating Curve= 0 ,0
Exp/Cntr(USF)=0,0
Exp/Cntr=0.3,0.1