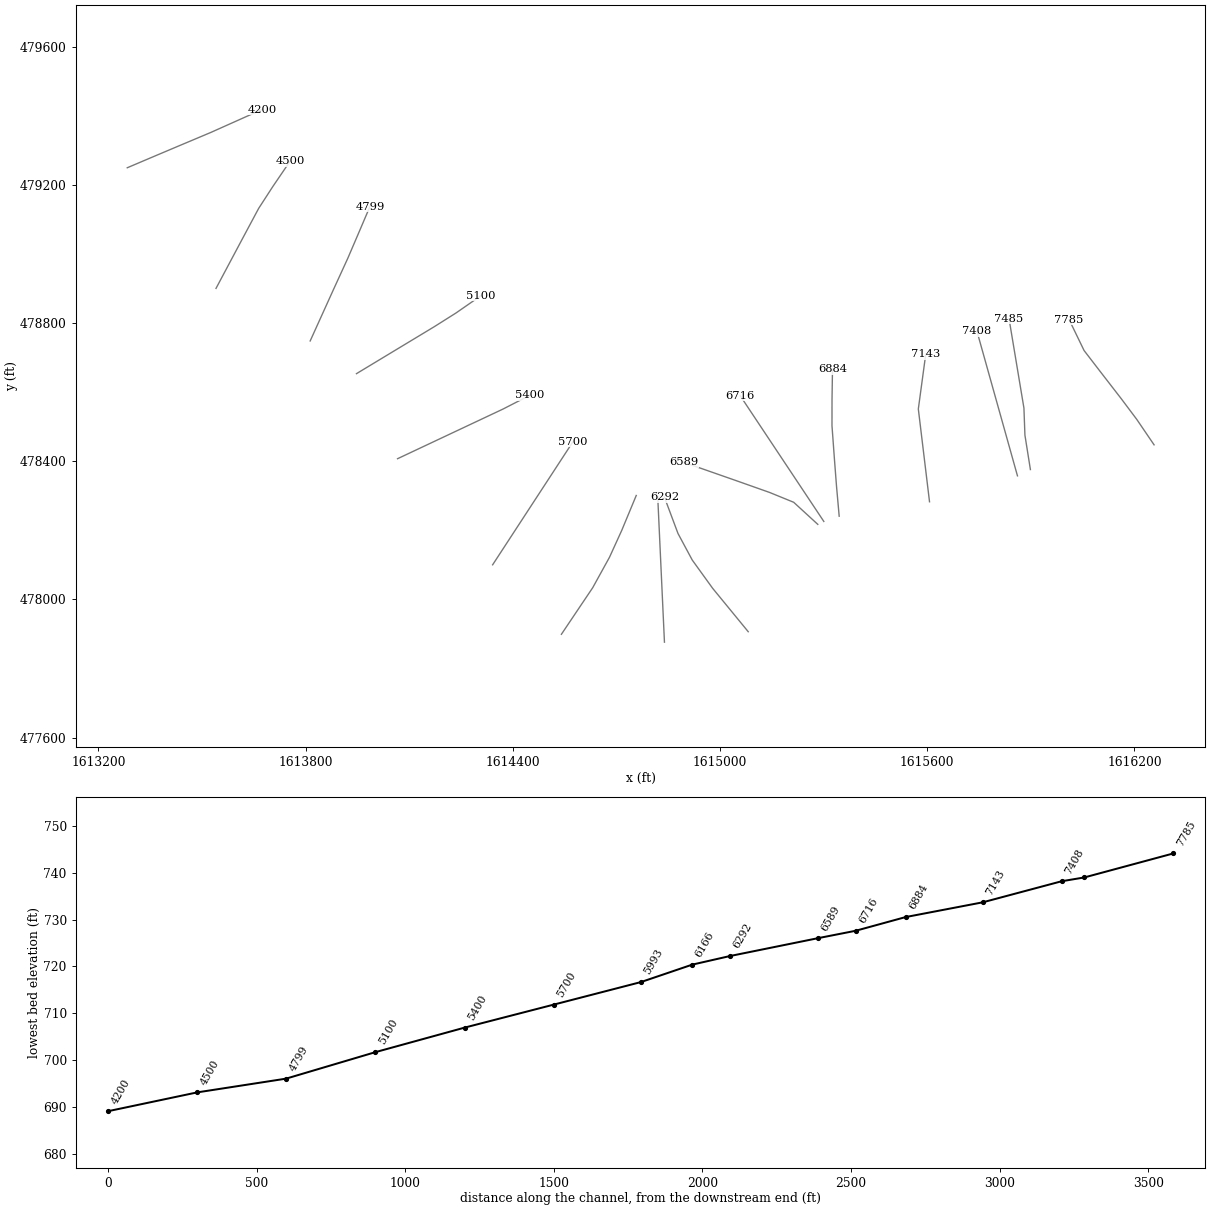
HEC-RAS study BgTrbbleCk.prj: BgTrbbleCk

--- BgTrbbleCk.g01 (geometry) --- (continued)

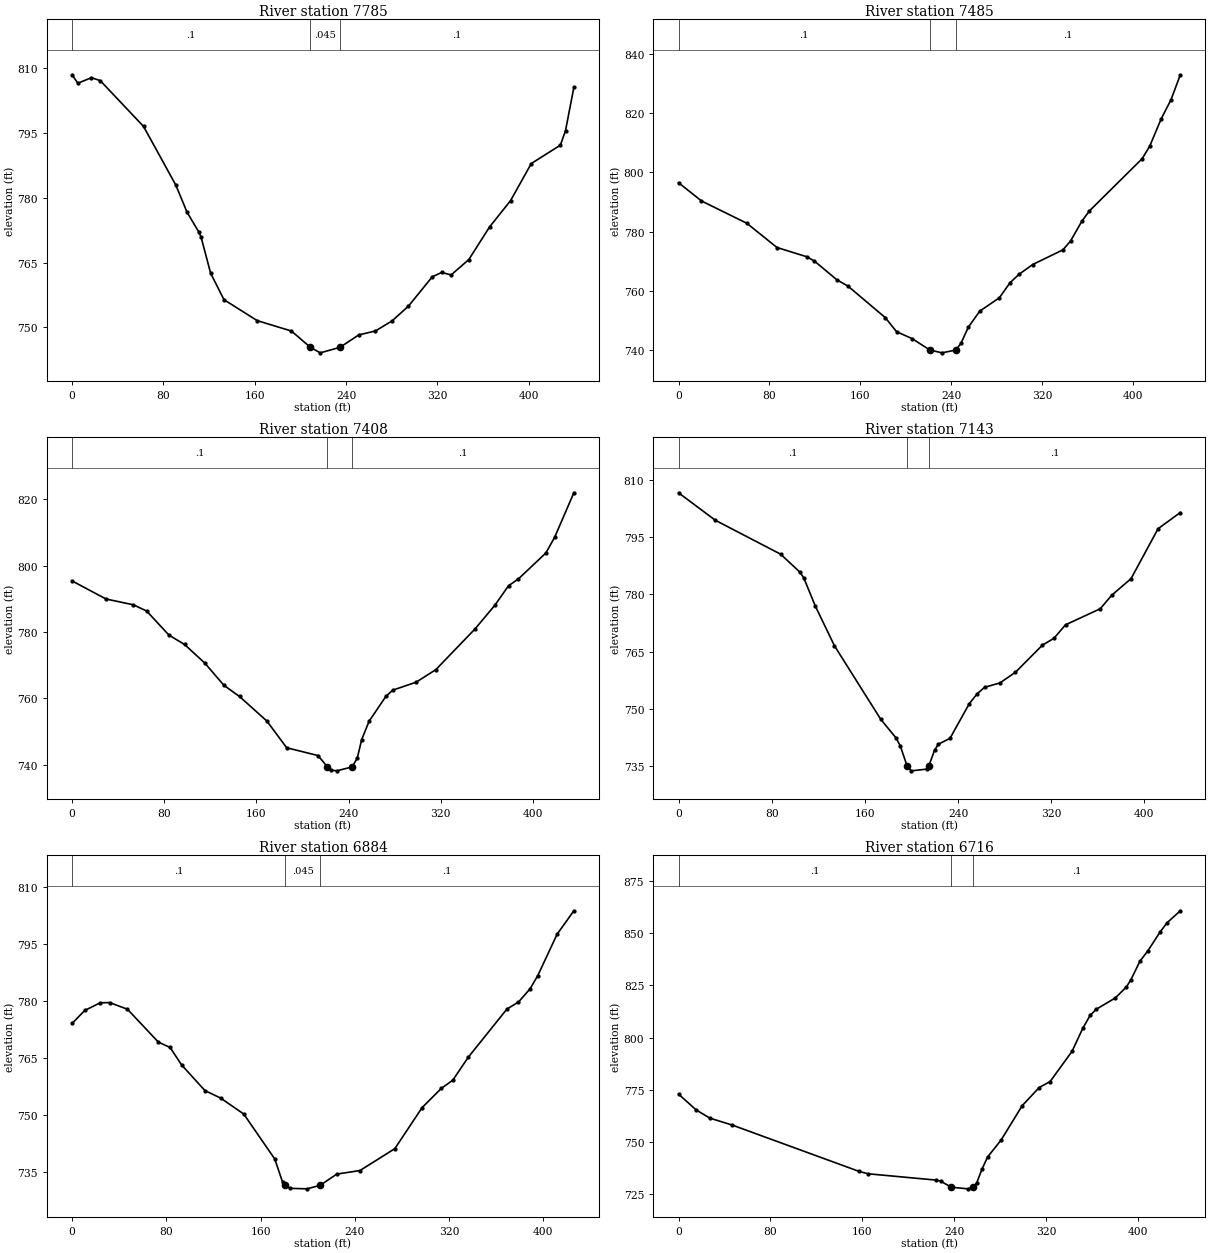
Type RM Length L Ch R = 1 ,7785    ,300.1,299.3,284.3
XS GIS Cut Line= 6
1616256.99045117478447.8580345961616206.89409468478521.483871594
1616161.89418468478581.4840796741616100.70795535478660.594157666
 1616054.2877726478720.9867534191616010.98241301 478810.43342492
#Sta/Elev= 30
       0  808.44     5.1  806.48      17  807.78    24.7  807.08    62.6   796.5
    90.9  782.92   100.7  776.66   110.8  772.18     113  770.91   121.4  762.53
   133.1  756.41   162.2  751.57   192.2  749.16  208.82745.3853   217.4  744.12
   234.6 745.385   251.2  748.27   265.8  749.18   280.5  751.54   294.6   754.9
   315.6  761.72   323.8  762.72   332.1  762.14   347.6  765.71   365.8  773.26
   384.1  779.31   402.3  787.91   427.8  792.16   432.3  795.53   439.6  805.52
#Mann= 3 ,-1,0
       0      .1       0  208.82    .045       0   234.6      .1       0
Bank Sta=208.82,234.6
XS Rating Curve= 0 ,0
Exp/Cntr(USF)=0,0
Exp/Cntr=0.3,0.1

Type RM Length L Ch R = 1 ,7485    ,75.9,76.9,78.4
XS GIS Cut Line= 6
1615898.85730918478376.2987945081615882.98004434478476.054172426
1615880.11915767478554.2718637591615863.67857376478652.911102176
  1615851.348874478726.8906130051615836.96307601478813.199823588
#Sta/Elev= 30
       0  796.52    20.2  790.34    60.1  782.81    86.7   774.6   113.1  771.46
   119.7  770.01   139.4  763.69   149.2  761.55   182.1  750.88     192  746.14
   205.5  743.84  221.32739.9453     232     739  244.03739.9454   248.6  742.17
   255.2  747.69   265.2  753.09   282.5  757.62   291.8  762.67   299.6  765.49
   311.8  768.85   338.4  773.81   345.2  776.82     355  783.44   361.7  786.96
   408.2  804.63   414.9  808.91     425  818.14   433.6  824.57   441.8     833
#Mann= 3 ,-1,0
       0      .1       0  221.32    .045       0  244.03      .1       0
Bank Sta=221.32,244.03
XS Rating Curve= 0 ,0
Exp/Cntr(USF)=0,0
Exp/Cntr=0.3,0.1

Type RM Length L Ch R = 1 ,7408    ,262.8,265.1,260.7
XS GIS Cut Line= 2
1615861.38743876478358.0534165981615743.91697871478777.345788604
#Sta/Elev= 30
       0   795.4    29.5  789.95    53.3   788.2    64.7  786.33      84   779.1
    97.6  776.25   115.2  770.64   131.7  763.97   145.3  760.58   169.1  753.16
   186.2  745.14   213.4  742.78  221.62739.3583   224.4  738.42   229.7  738.18
     243  739.37   247.5  742.01   251.2   747.5   257.7  753.11   272.3  760.61
   278.2  762.48   298.6   764.9   315.7  768.69   349.7  780.96   366.8  788.05
   378.7  793.94   387.2  795.98   411.1  803.82   418.7  808.53   435.4  821.96
#Mann= 3 ,-1,0
       0      .1       0  221.62    .045       0     243      .1       0
Bank Sta=221.62,243
XS Rating Curve= 0 ,0
Exp/Cntr(USF)=0,0
Exp/Cntr=0.3,0.1

Type RM Length L Ch R = 1 ,7143    ,261,259.7,258.2
XS GIS Cut Line= 3
1615606.72272284478282.9682725071615574.30238794 478551.64171731
1615595.81395201 478710.45855926
#Sta/Elev= 30
       0   806.7    31.5   799.5    87.7  790.57   104.2  785.87   107.5  784.39
   117.4  776.99   133.9  766.52   173.6  747.24   186.8  742.31   190.4  740.26
   196.3  734.92     200  733.69   213.3  734.15  214.85  734.91   219.9  739.15
   223.2  740.69   233.1  742.22   249.6  751.28   256.2  753.84   262.8  755.63
     276  756.77   289.3  759.57   312.5   766.7   322.4   768.5   332.3  772.03
   362.1  776.24   372.1  779.83   388.6  784.16   411.8  797.27   430.9  801.52
#Mann= 3 ,-1,0
       0      .1       0   196.3    .045       0  214.85      .1       0
Bank Sta=196.3,214.85
XS Rating Curve= 0 ,0
Exp/Cntr(USF)=0,0
Exp/Cntr=0.3,0.1

Type RM Length L Ch R = 1 ,6884    ,162.8,167.9,171.7
XS GIS Cut Line= 6
1615345.11366601478241.1829230041615337.32267109478328.717196763
1615331.57137026478403.4962466661615324.27315651478503.230299175
1615324.35517734478578.4581670911615325.73345542478666.314618677
#Sta/Elev= 30
       0  774.02    10.8  777.44    23.9  779.44    31.9   779.5      47  777.75
    73.3   769.1    83.2   767.7    93.1  763.07   112.8  756.37   126.1   754.4
   145.8  750.19   172.1  738.37   178.7  732.32  180.71731.4686   185.2  730.67
   199.5  730.54  210.59731.4694   224.7  734.41   244.4  735.35     274   741.1
   297.1  751.87   313.5  756.95   323.2  759.09   336.4  765.15   369.2  777.81
     379  779.64   388.9  783.15   395.4  786.61   411.8  797.48     426  803.63
#Mann= 3 ,-1,0
       0      .1       0  180.71    .045       0  210.59      .1       0
Bank Sta=180.71,210.59
XS Rating Curve= 0 ,0
Exp/Cntr(USF)=0,0
Exp/Cntr=0.3,0.1

Type RM Length L Ch R = 1 ,6716    ,119.9,126.8,133.8
XS GIS Cut Line= 2
1615300.61604552478226.0063301171615058.81553651478589.564542245
#Sta/Elev= 30
       0  772.98    15.3  765.41    27.2  761.48    46.9  758.12   157.2  735.95
   165.1  734.82   224.2   731.8   228.1  731.31   237.2  728.41   251.8  727.62
  256.45 728.425   259.4  730.42   264.1  737.14   268.9  742.86   280.7  751.01
     299  767.45   313.8  776.12   323.3  778.99   342.4  793.47   351.7  804.44
   358.1  810.64   363.5  813.62   380.1  819.03   389.6  824.24   393.6  827.71
   401.4  836.54   408.5  841.69     419  850.61   425.1  855.03   436.6  860.75
#Mann= 3 ,-1,0
       0      .1       0   237.2    .045       0  256.45      .1       0
Bank Sta=237.2,256.45
XS Rating Curve= 0 ,0
Exp/Cntr(USF)=0,0
Exp/Cntr=0.3,0.1

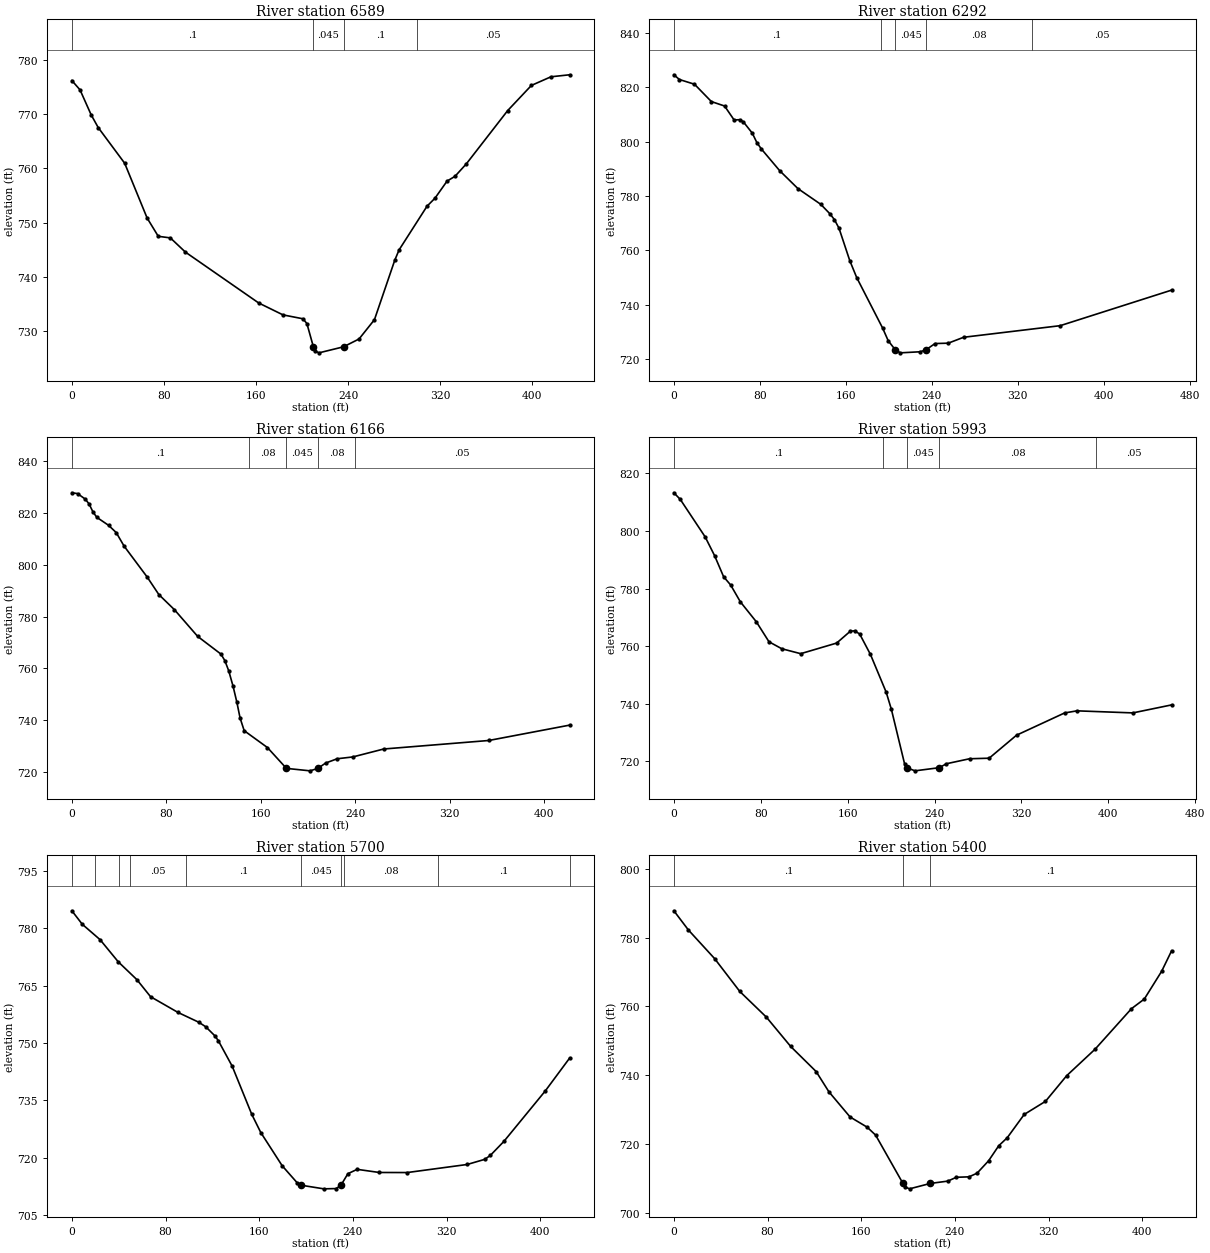
Type RM Length L Ch R = 1 ,6589    ,300.8,296.8,283
XS GIS Cut Line= 6
1615283.13872434478217.5842169231615213.37278776478281.519456506
1615143.50153643478309.9961055821615049.20579326478343.328059927
1614978.41623667478368.1042570921614895.82847534478397.009383008
#Sta/Elev= 30
       0  776.19     7.1  774.47    16.8  769.86    22.9  767.53    45.9  760.96
    65.4  750.87    75.1   747.5    85.6  747.21    98.7  744.59   162.4  735.22
   183.5  733.03   200.9  732.31   204.3  731.42   209.9727.1535   211.3  726.39
   214.8  726.04  236.12727.1512   249.6  728.59     263  732.15   280.6  743.07
   284.4     745   308.7  753.05   315.6  754.52   326.1  757.67     333  758.55
   342.8  760.83   378.8  770.66   399.4  775.29   416.4  776.88   432.6  777.25
#Mann= 4 ,-1,0
       0      .1       0   209.9    .045       0  236.12      .1       0
   300.1     .05       0
Bank Sta=209.9,236.12
XS Rating Curve= 0 ,0
Exp/Cntr(USF)=0,0
Exp/Cntr=0.3,0.1

Type RM Length L Ch R = 1 ,6292    ,130,126.6,112
XS GIS Cut Line= 6
1615081.71524267477906.7045893371615026.24094418477974.371776834
1614978.69149859478032.3719889221614919.62140676478114.222218916
1614878.38887767478190.9950312531614838.88239501 478296.58996442
#Sta/Elev= 30
       0  824.59     5.2  822.84    19.2  821.11    34.9  814.73    47.2  813.09
    56.1  807.94    61.1  808.06    64.6   807.3      73   803.1    77.3  799.59
    81.5  797.25    98.5  789.28   115.5  782.68   136.7  776.91   145.2  773.43
   149.4  771.29   153.7  768.12   163.7  756.21   170.2  749.92   194.3  731.35
   199.5  726.69  205.97 723.402   210.8  722.22   229.5  722.62  234.91723.4009
   243.1  725.64   255.4  725.78   269.7  727.95   359.6  732.22   463.3  745.31
#Mann= 5 ,-1,0
       0      .1       0   192.5     .08       0  205.97    .045       0
  234.91     .08       0  333.44     .05       0
Bank Sta=205.97,234.91
XS Rating Curve= 0 ,0
Exp/Cntr(USF)=0,0
Exp/Cntr=0.3,0.1

Type RM Length L Ch R = 1 ,6166    ,177.3,172.1,161.1
XS GIS Cut Line= 2
1614839.12028583477876.4021968161614819.62810968478297.649781464
#Sta/Elev= 30
       0  827.87     4.8  827.56    11.3  825.44    14.6  823.55    17.9  820.44
    21.2  818.36    31.1  815.29    37.6  812.48    44.2  807.29    63.9  795.24
    73.7  788.52    86.9  782.68   106.6  772.35   126.3  765.52   129.6     763
   132.9  759.06   136.6  753.05   139.8  746.91   142.5  740.85     146  735.91
   165.7  729.39  181.78721.3403   201.8  720.39  208.46721.3402     215   723.4
   224.8  725.06     238  725.76   264.2  728.83   353.2  732.12   421.7  738.06
#Mann= 5 ,-1,0
       0      .1       0     150     .08       0  181.78    .045       0
  208.46     .08       0     240     .05       0
Bank Sta=181.78,208.46
XS Rating Curve= 0 ,0
Exp/Cntr(USF)=0,0
Exp/Cntr=0.3,0.1

Type RM Length L Ch R = 1 ,5993    ,291.4,293.4,290.2
XS GIS Cut Line= 6
1614540.67433001477899.2403654161614589.49083342477971.857346177
1614631.33359751478034.1003319171614680.02542926478122.410850838
1614715.53093567478200.3250650911614757.45342401478301.254981339
#Sta/Elev= 30
       0   813.3     5.9     811    28.8  797.98    37.5  791.45    45.8  784.13
    52.3  781.25    61.2  775.42    75.9  768.49    87.6  761.52    99.4   759.1
   116.8  757.39   149.9  761.08   162.5  765.21   166.5  765.33   171.1  764.22
     181  757.13   195.5     744   200.3  738.02   212.4  719.16  214.44 717.772
     222  716.68  244.33717.7734     251  719.15   272.3  720.88   290.3  721.07
   315.5  729.06   359.8   736.8   371.2  737.53   422.6  736.81   458.3  739.59
#Mann= 5 ,-1,0
       0      .1       0   192.5     .08       0  214.44    .045       0
  244.33     .08       0  388.97     .05       0
Bank Sta=214.44,244.33
XS Rating Curve= 0 ,0
Exp/Cntr(USF)=0,0
Exp/Cntr=0.3,0.1

Type RM Length L Ch R = 1 ,5700    ,309.1,300,293.6
XS GIS Cut Line= 6
1614341.55136867478100.4499367621614389.37082684478173.728333503
1614430.35926193478236.5389034151614485.01925759478320.274628341
1614526.00703651478383.0838859231614573.82616659478456.361298427
#Sta/Elev= 30
       0  784.62     8.9  781.09    24.1  777.06    39.6  771.27    55.5  766.61
    67.2  762.14    90.7  758.01   108.5  755.44   114.3  754.27   122.1  751.91
   125.1  750.61   136.9  743.96   153.6  731.37   161.3  726.61   179.6   717.9
   192.6  713.38  195.35712.8372   215.1  711.87   225.7  711.94  229.79712.8348
   235.7  715.83   243.6  716.97   262.5  716.15   286.3  716.13   337.5  718.24
   352.6  719.59   357.4  720.64   368.9  724.28   404.2  737.47     425  746.07
#Mann= 10 ,-1,0
       0      .1       0      20     .05       0      40      .1       0
      50     .05       0    97.5      .1       0  195.35    .045       0
  229.79      .1       0   232.5     .08       0   312.5      .1       0
     425     .08       0
Bank Sta=195.35,229.79
XS Rating Curve= 0 ,0
Exp/Cntr(USF)=0,0
Exp/Cntr=0.3,0.1

Type RM Length L Ch R = 1 ,5400    ,298,300,301
XS GIS Cut Line= 6
1614066.22088259478407.6786530021614145.38542242478444.951216251
1614213.24060167478476.899315089  1614303.714174478519.496998921
1614371.56902517478551.4447696661614449.46552293478591.410897091
#Sta/Elev= 30
       0  787.83    12.4  782.25    34.8  773.92    56.3  764.37      79   756.9
    99.8  748.36   121.5  741.08   132.4  735.19   150.5  727.86   165.1  724.89
   172.3  722.59  195.66708.5282   197.7  707.48   201.3  706.96  218.98708.5297
     234  709.21   241.2  710.32   252.1  710.45     259  711.52   268.8  715.12
   277.5  719.51   284.7  721.81   299.2  728.59   317.4  732.41   335.5  739.87
   359.8  747.59   390.8  759.35   401.8  762.16   416.6  770.23   425.1  776.19
#Mann= 3 ,-1,0
       0      .1       0  195.66    .045       0  218.98      .1       0
Bank Sta=195.66,218.98
XS Rating Curve= 0 ,0
Exp/Cntr(USF)=0,0
Exp/Cntr=0.3,0.1

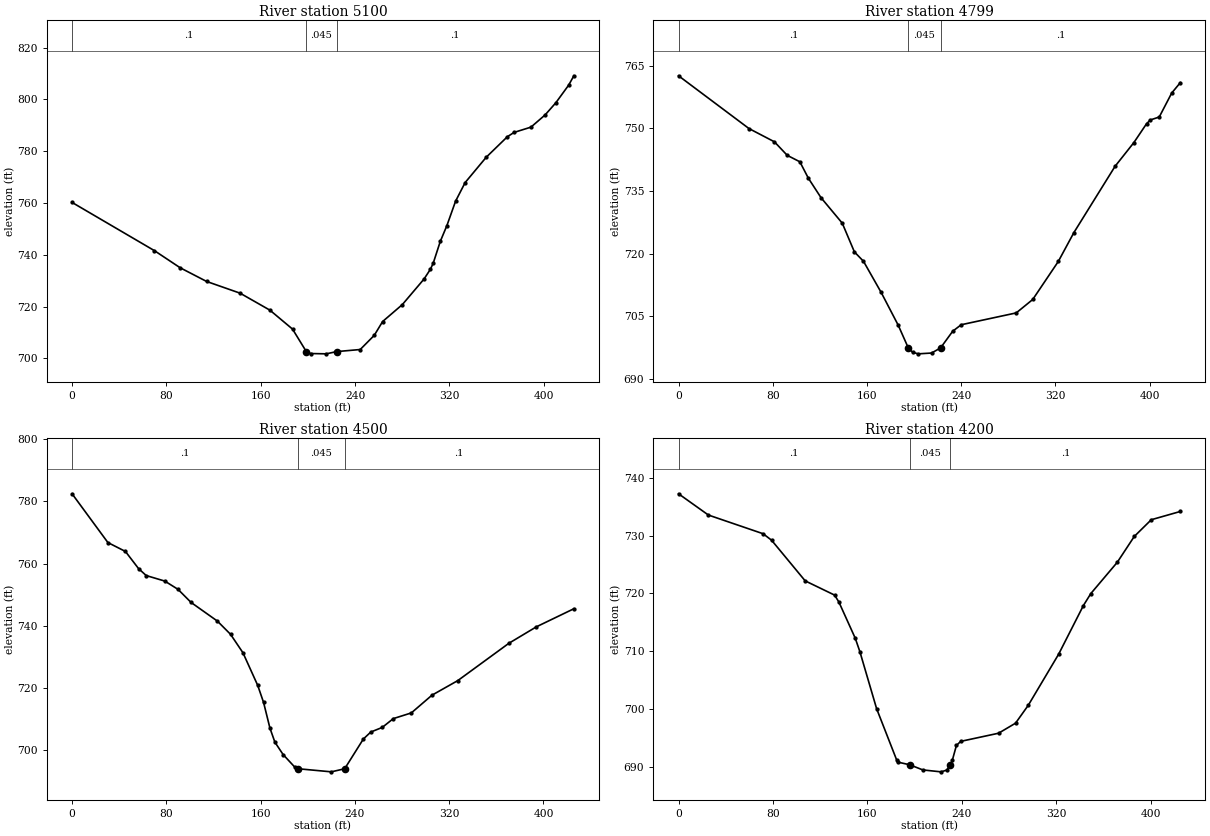
Type RM Length L Ch R = 1 ,5100    ,291.2,301,307.2
XS GIS Cut Line= 6
1613947.22505759478653.9612969161614022.13534084478699.179382339
   1614086.34453478737.937835008 1614171.9568916478789.614568919
1614235.40886442478829.6266280111614307.76173809478879.814519763
#Sta/Elev= 30
       0  760.21    69.9  741.57    91.7  734.97   114.1  729.69   142.5  725.16
   167.8   718.6     187  711.28  198.68 702.598   202.3  701.85   215.6  701.73
  224.41702.5975   244.4   703.4   256.3  708.87   263.4  714.21   280.1  720.74
   298.5  730.61   303.9  734.38   306.3  736.72   312.3  745.15   317.9  751.25
   325.3  760.72   333.4  767.89   351.3  777.68   369.2  785.59   374.9  787.26
   389.2  789.29   401.2     794   410.3   798.7   421.2  805.52   425.6  809.13
#Mann= 3 ,-1,0
       0      .1       0  198.68    .045       0  224.41      .1       0
Bank Sta=198.68,224.41
XS Rating Curve= 0 ,0
Exp/Cntr(USF)=0,0
Exp/Cntr=0.3,0.1

Type RM Length L Ch R = 1 ,4799    ,300,298.9,298.7
XS GIS Cut Line= 6
1613813.16889526478748.6363044231613849.26921676478828.312982336
1613880.22158268478896.6284625081613921.96428134478987.706692427
1613951.68633476479056.9906745851613986.23875909479137.890119091
#Sta/Elev= 30
       0  762.57    59.8  749.95    81.4  746.78    92.3  743.54     103     742
   110.2  738.08     121   733.4     139  727.32   149.3  720.45     157  718.21
     172  710.77   186.5  702.92  195.06697.4841   198.8  696.43   203.5  696.07
   214.8  696.26  222.44697.4838   232.8  701.49     240  703.03   286.7  705.86
   300.7  709.07   322.4  718.16   335.6  725.05   370.6  740.92   386.6  746.61
   397.3  751.09   400.6  752.01   408.1  752.71   418.7  758.45     426  760.93
#Mann= 3 ,-1,0
       0      .1       0  195.06    .045       0  222.44      .1       0
Bank Sta=195.06,222.44
XS Rating Curve= 0 ,0
Exp/Cntr(USF)=0,0
Exp/Cntr=0.3,0.1

Type RM Length L Ch R = 1 ,4500    ,313.2,300.4,287.2
XS GIS Cut Line= 6
1613540.49194717478900.9033883361613581.60374159 478978.14371942
1613616.84218818479044.3499518331613663.99891801479132.533174425
1613704.91451859479195.7177593411613754.45641425479268.470894679
#Sta/Elev= 30
       0  782.41    30.4  766.75    45.3  763.89    56.4   758.4    62.9  756.16
    78.7  754.38    89.9  751.73     101  747.52   123.3  741.54   134.5  737.28
     145  731.37   157.5  720.93   162.5  715.43   167.9  707.18   172.1  702.67
   179.1  698.68     189  694.65  191.96694.1298     220  693.14  231.33694.1298
   247.2  703.69   253.5  705.92   263.2   707.4   272.6  710.23   287.9  712.06
   305.4  717.75   327.3  722.43   370.7  734.42     394   739.7   425.8   745.5
#Mann= 3 ,-1,0
       0      .1       0  191.96    .045       0  231.33      .1       0
Bank Sta=191.96,231.33
XS Rating Curve= 0 ,0
Exp/Cntr(USF)=0,0
Exp/Cntr=0.3,0.1

Type RM Length L Ch R = 1 ,4200    ,247.3,257.5,266.1
XS GIS Cut Line= 6
1613283.48360293479250.2448812571613364.09794301479284.486610666
1613433.24609867479313.7021034211613525.42176734479352.484834254
1613593.89308709479383.1150223461613673.75250742 479418.83837609
#Sta/Elev= 30
       0  737.23    25.3  733.55    71.6  730.32    78.8   729.2   107.3  722.16
   132.2   719.7   135.8  718.52   149.7  712.24   153.6  709.93   167.8  700.05
   184.7  691.22   185.6  690.81  195.73690.3496     207  689.45   222.3  689.12
   227.3  689.42  230.29690.3501   231.9  691.09   235.4  693.68     239  694.39
   271.1   695.8   285.5  697.54   296.3  700.64     322  709.47     343   717.9
   349.3  719.97   371.7  725.38   386.1  729.85   400.5  732.74   425.1  734.17
#Mann= 3 ,-1,0
       0      .1       0  195.73    .045       0  230.29      .1       0
Bank Sta=195.73,230.29
XS Rating Curve= 0 ,0
Exp/Cntr(USF)=0,0
Exp/Cntr=0.3,0.1