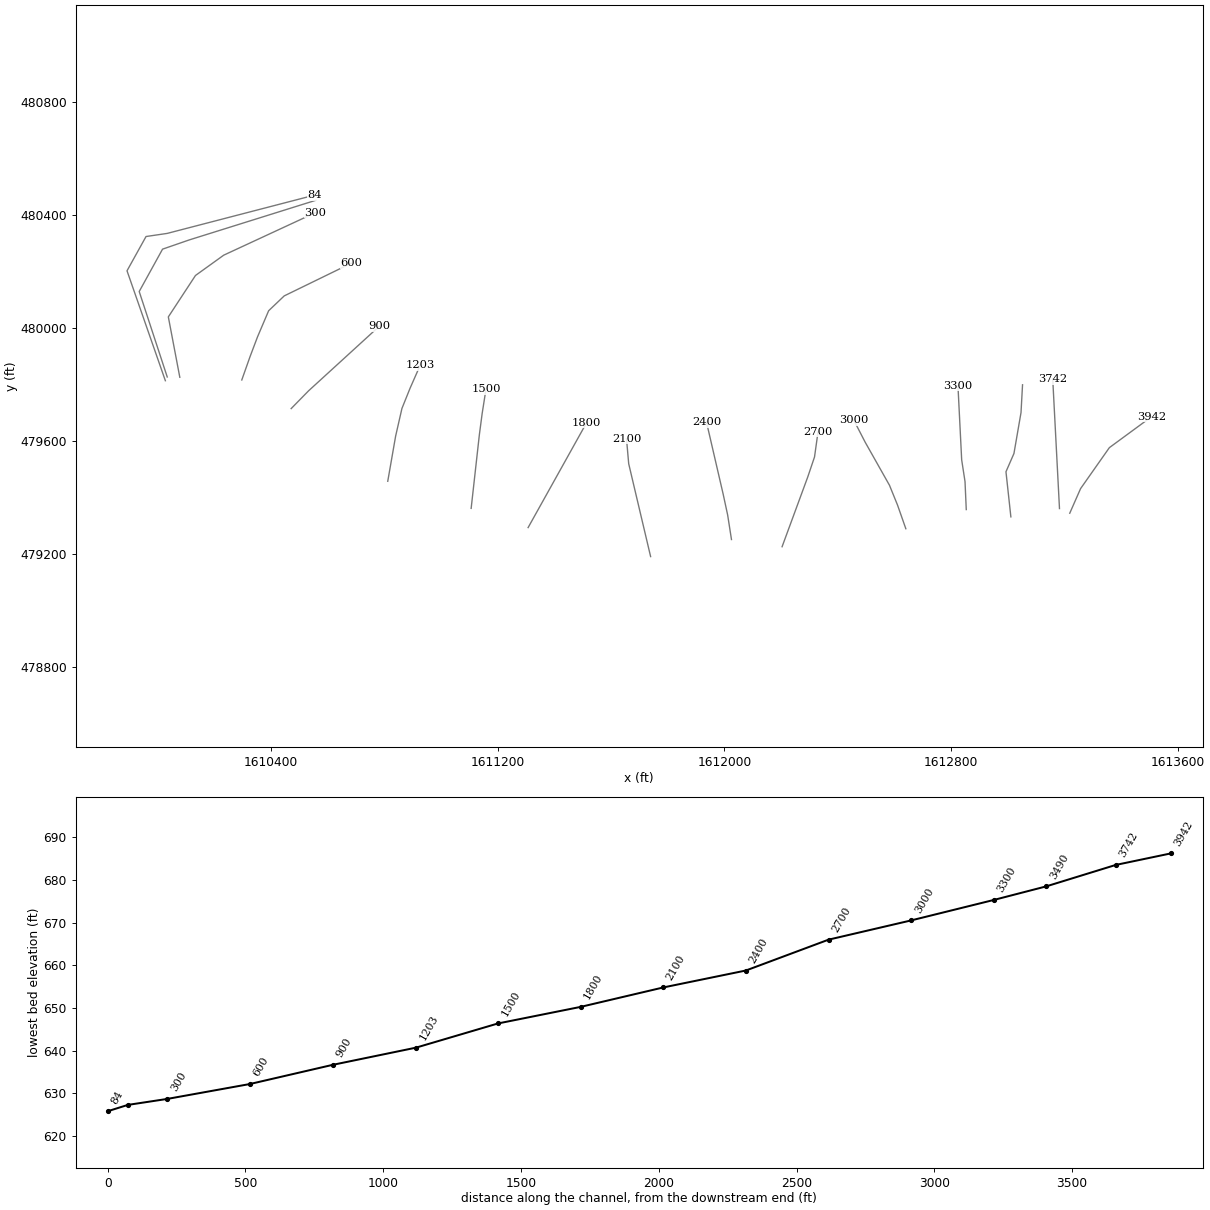
HEC-RAS study BgTrbbleCk.prj: BgTrbbleCk

--- BgTrbbleCk.g01 (geometry) --- (continued)

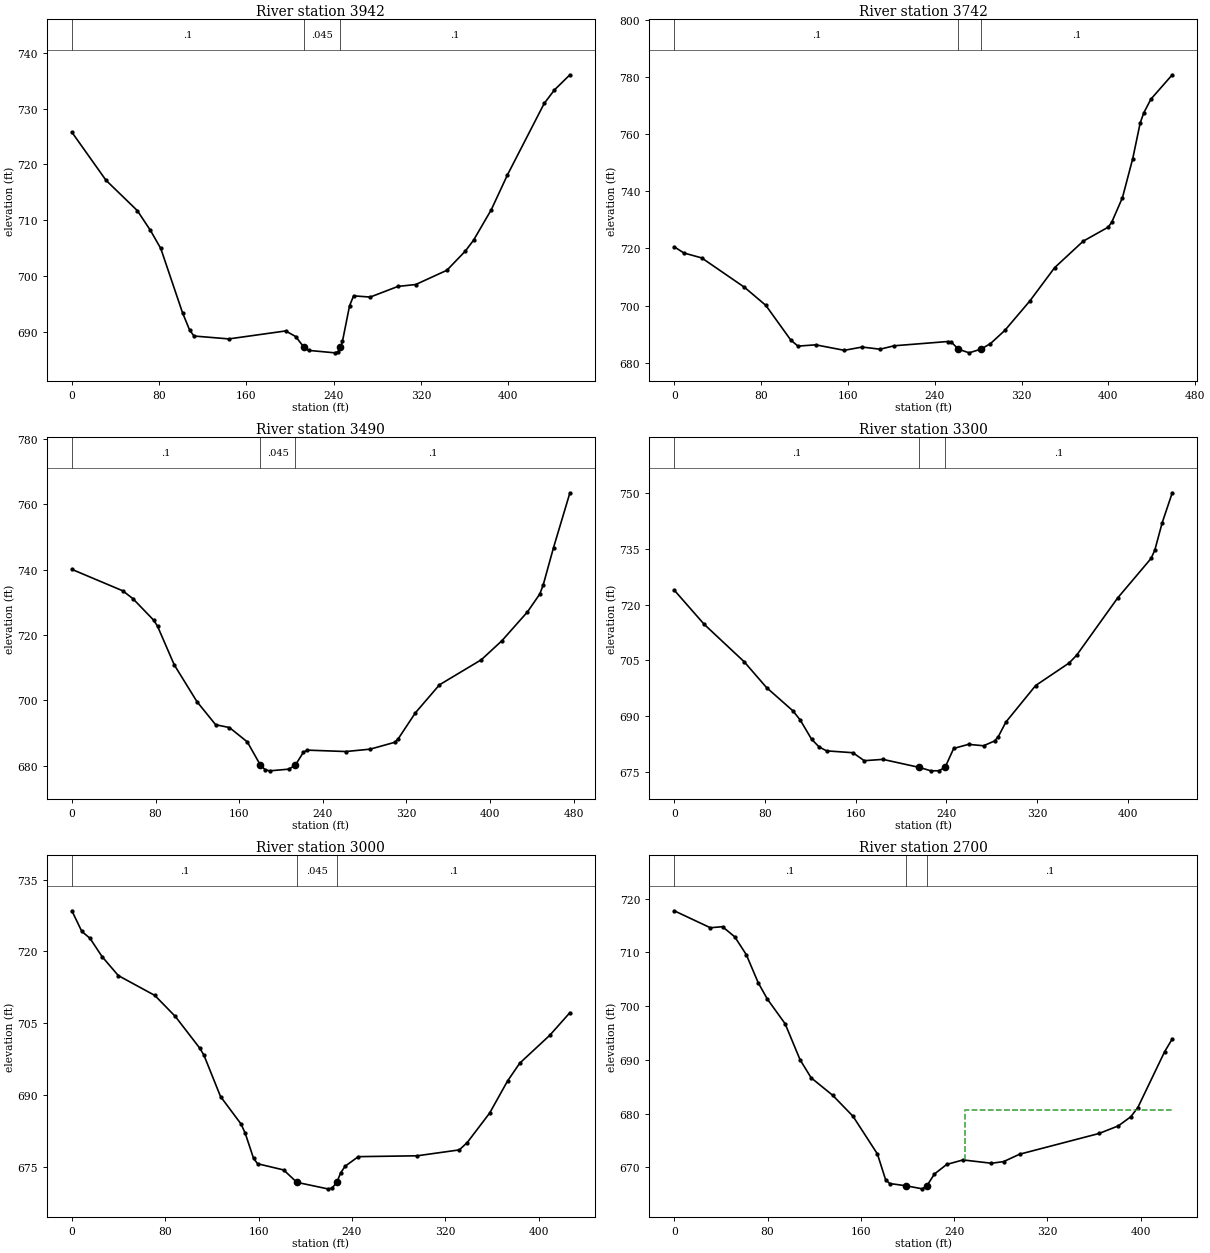
Type RM Length L Ch R = 1 ,3942    ,189.9,200,204.9
XS GIS Cut Line= 4
1613217.61857717479345.2614234981613255.78425013479432.316256058
1613357.28911744479577.295654854 1613505.8748075 479686.76613961
#Sta/Elev= 30
       0  725.79    31.3  717.16      60  711.72      72  708.17    81.5  704.92
   101.5  693.35   107.9   690.3   111.9  689.21   143.9  688.69     196  690.12
   205.2  689.11  212.92 687.152     217  686.63   241.2  686.19   244.1  686.41
  246.18687.1508   248.1  688.29   254.6  694.66   258.3  696.42   273.5   696.2
   298.9  698.11   315.2  698.45   343.8  701.01   360.6  704.43   368.2  706.39
   384.5  711.88   399.3  718.12     433  730.95   442.4  733.38   456.6   736.1
#Mann= 3 ,-1,0
       0      .1       0  212.92    .045       0  246.18      .1       0
Bank Sta=212.92,246.18
XS Rating Curve= 0 ,0
Exp/Cntr(USF)=0,0
Exp/Cntr=0.3,0.1

Type RM Length L Ch R = 1 ,3742    ,250.6,252.4,223.8
XS GIS Cut Line= 2
1613181.41944715479361.7846454891613157.60143011479820.043293375
#Sta/Elev= 30
       0  720.58     8.9  718.42    25.3   716.7    64.7  706.43    84.4   700.1
   107.4  687.96     114  685.84   130.4  686.29   156.7  684.37   173.1  685.52
   189.6  684.76   202.7  685.96     252  687.45   255.3  687.24  261.86684.7752
   271.7  683.49   282.6  684.78   291.4  686.72   304.6  691.33   327.6   701.6
   350.5  713.28   376.8  722.54   399.8  727.44   403.1  729.15     413  737.78
   422.5  751.46   429.4     764   432.7  767.47   439.2  772.23   458.9  780.76
#Mann= 3 ,-1,0
       0      .1       0  261.86    .045       0   282.6      .1       0
Bank Sta=261.86,282.6
XS Rating Curve= 0 ,0
Exp/Cntr(USF)=0,0
Exp/Cntr=0.3,0.1

Type RM Length L Ch R = 1 ,3490    ,184.5,189.8,195.6
XS GIS Cut Line= 5
1613009.99406214479332.3686304121612992.73340362479491.986524466
1613020.88109513479556.671635779 1613045.7882637479701.476731729
1613051.15152344 479799.74235777
#Sta/Elev= 30
       0  740.04    48.6   733.5    58.3  731.12    78.1  724.56    81.9  722.69
    97.9  710.87   119.7  699.59   137.5  692.57   150.7   691.7   167.8  687.32
  180.29 680.244   184.8  678.83   189.2  678.47   207.6  678.99   213.8680.2417
   221.4  684.12     225   684.8   262.1  684.37   285.4   685.1   308.7  687.18
     312  688.19   328.6  696.21   351.6  704.76   391.7  712.43   411.4  718.25
   435.8  727.05   447.6  732.52   450.9  735.35   460.7  746.67   476.4  763.45
#Mann= 3 ,-1,0
       0      .1       0  180.29    .045       0   213.8      .1       0
Bank Sta=180.29,213.8
XS Rating Curve= 0 ,0
Exp/Cntr(USF)=0,0
Exp/Cntr=0.3,0.1

Type RM Length L Ch R = 1 ,3300    ,292.1,300,304.6
XS GIS Cut Line= 6
1612852.73512059 479358.185610251612848.35684851479457.075832427
1612836.56914243479534.0349960921612831.56029418479633.909468248
1612827.80800509479708.8154864161612823.43006109479796.205731586
#Sta/Elev= 30
       0  723.87    26.4  714.69    61.7  704.62    81.4  697.69   104.6  691.45
   111.1  688.98   121.1  683.83   127.7  681.74   134.4  680.67   157.6  680.17
   167.6  678.03   184.1  678.38  216.15676.2232   226.5   675.3   233.4  675.32
   238.9676.2225   246.5  681.32   259.6  682.42   272.8  682.04   282.6  683.33
   285.9  684.51   292.5  688.39   318.8  698.23   348.3  704.28   354.9  706.35
     391  721.71   420.6  732.38   423.9  734.62   430.4  741.96   439.3  750.03
#Mann= 3 ,-1,0
       0      .1       0  216.15    .045       0   238.9      .1       0
Bank Sta=216.15,238.9
XS Rating Curve= 0 ,0
Exp/Cntr(USF)=0,0
Exp/Cntr=0.3,0.1

Type RM Length L Ch R = 1 ,3000    ,313,300,293.9
XS GIS Cut Line= 6
1612639.63351268479290.4311525821612610.37569718479374.138990417
1612581.99353608479444.2254644191612532.96705934479531.382770419
1612496.19744784 479596.751078011612456.16307908479674.624609917
#Sta/Elev= 30
       0  728.48     8.5  724.18    15.5  722.75    25.9  718.92    39.8  714.97
    71.1  710.83    88.7  706.44   109.7  699.81   113.2  698.37   127.4  689.76
   145.1  683.99   148.6  682.08   155.7  676.88   159.2  675.74   181.5  674.45
  192.84671.8668   219.2  670.51   222.9  670.63  227.08671.8654   230.4  673.84
   234.2  675.22   245.5  677.22     296   677.4   332.1  678.63   338.9  680.17
   358.1  686.31   373.4  692.98   383.9  696.71   409.7  702.54   426.9  707.25
#Mann= 3 ,-1,0
       0      .1       0  192.84    .045       0  227.08      .1       0
Bank Sta=192.84,227.08
XS Rating Curve= 0 ,0
Exp/Cntr(USF)=0,0
Exp/Cntr=0.3,0.1

Type RM Length L Ch R = 1 ,2700    ,294.6,300,304.8
XS GIS Cut Line= 6
1612203.37585501479226.7698625921612233.49817009479308.921601176
1612259.31701609479379.3374708441612293.74214409479473.225406423
 1612317.7122405479544.3187681731612330.06785885479632.970493749
#Sta/Elev= 30
       0  717.75      31  714.59    41.4  714.79    51.9   712.9    61.8  709.58
      72  704.36    79.9   701.3    95.1  696.72   107.9  690.02   117.4  686.66
   135.8  683.42   153.3   679.5   174.2  672.49   181.2  667.72   184.7  666.99
   198.7  666.57   212.7     666  216.63666.5728   223.1  668.76   233.6  670.54
   247.6  671.38     272  670.76   282.4  671.07   296.2  672.45   364.2   676.3
   380.8  677.72   391.4  679.41   397.4   681.1   420.5  691.54     427  693.91
#Mann= 3 ,-1,0
       0      .1       0   198.7    .045       0  216.63      .1       0
#XS Ineff= 2 , 0
                          249.17          680.74
Permanent Ineff=
       F       F
Bank Sta=198.7,216.63
XS Rating Curve= 0 ,0
Exp/Cntr(USF)=0,0
Exp/Cntr=0.3,0.1

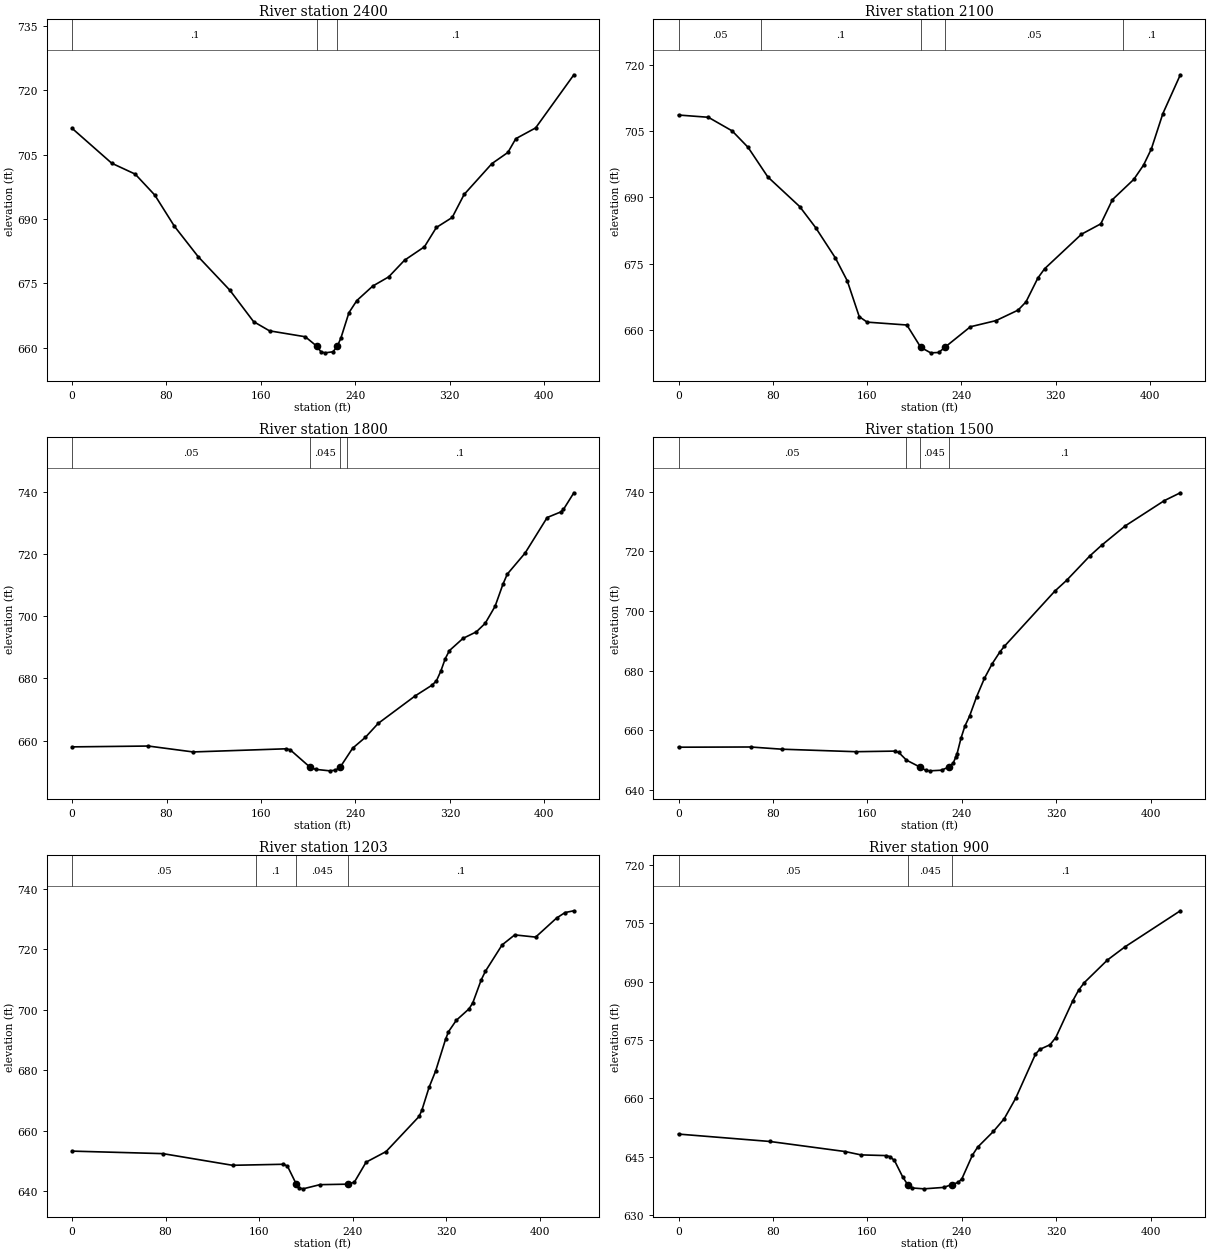
Type RM Length L Ch R = 1 ,2400    ,299.9,300,300.1
XS GIS Cut Line= 6
1612024.92181559   479252.1572791612011.44874543479338.847722426
1611995.72994484479412.1917358341611973.24376935479509.630517334
1611956.37930176479582.7100955841611936.70381618479667.969111428
#Sta/Elev= 30
       0  711.13    33.6  702.99    53.5  700.45    70.1  695.56    86.7   688.3
   106.8  681.22   133.7  673.38   153.8  666.06   167.3  663.91   197.6  662.53
  207.48 660.307     211  658.98   214.4  658.78   221.1  659.03  224.76660.3055
   227.9  662.31   234.6  668.14   241.3  670.97   254.8  674.35   268.3  676.49
   281.7  680.37   298.6  683.51   308.7  688.01   322.1  690.34   332.2   695.7
   355.8  702.91   369.3   705.5     376  708.71   392.8  711.22   425.2  723.61
#Mann= 3 ,-1,0
       0      .1       0  207.48    .045       0  224.76      .1       0
Bank Sta=207.48,224.76
XS Rating Curve= 0 ,0
Exp/Cntr(USF)=0,0
Exp/Cntr=0.3,0.1

Type RM Length L Ch R = 1 ,2100    ,305.6,300,289.3
XS GIS Cut Line= 6
1611739.80854067479191.8565465961611719.76789834479277.030588835
1611702.58978309479350.0366764221611679.68595751479447.378345251
1611662.53769784479520.3916506771611654.79230651479608.458731756
#Sta/Elev= 30
       0  708.64    25.3  708.13    45.5  705.05      59  701.33    75.8  694.62
   102.8  687.93   116.3  683.18   133.1   676.3   143.2  671.12   153.4  662.99
   160.1  661.76   193.8  661.11   205.6  656.05     214  654.81   220.9  654.89
  225.99656.0504   247.7  660.71   269.4   662.1   288.2  664.48   294.9  666.34
     305  671.75   310.7  673.84     342  681.66   358.4  684.01   368.3  689.49
   386.4  694.07   394.7  697.31   401.3  700.96   411.1  708.98   425.9  717.75
#Mann= 5 ,-1,0
       0     .05       0      70      .1       0   205.6    .045       0
  225.99     .05       0   377.5      .1       0
Bank Sta=205.6,225.99
XS Rating Curve= 0 ,0
Exp/Cntr(USF)=0,0
Exp/Cntr=0.3,0.1

Type RM Length L Ch R = 1 ,1800    ,295.9,300,305.6
XS GIS Cut Line= 6
1611307.90356459479294.466249511 1611350.3975741479370.954941675
1611386.82105768 479436.516490341611435.38526501479523.932326004
1611471.80874859479589.493874669   1611514.30243479665.982894927
#Sta/Elev= 30
       0  657.97    64.6  658.24   102.5  656.34     181  657.35   184.7  657.05
  201.54  651.43   206.2  650.74   218.3  650.26   223.1  650.49  227.06651.4305
   237.6  657.53   248.5  661.07   259.3  665.53   290.7   674.4   304.8  677.81
   308.6  679.22   312.3  682.33   316.1  686.38   319.6  688.95   331.1  692.88
   342.4  694.98   349.9  697.72   358.3  703.22   364.9  710.27   368.6  713.55
   383.7  720.33   402.4  731.77   413.7  733.53   416.2  734.38     425  739.73
#Mann= 4 ,-1,0
       0     .05       0  201.54    .045       0  227.06     .05       0
   232.5      .1       0
Bank Sta=201.54,227.06
XS Rating Curve= 0 ,0
Exp/Cntr(USF)=0,0
Exp/Cntr=0.3,0.1

Type RM Length L Ch R = 1 ,1500    ,296.3,297.4,296
XS GIS Cut Line= 6
 1611107.0437301479362.4467565861611116.70644042 479449.41147767
1611124.98956034479523.9526671771611136.03350151479623.340919837
1611145.80579168479697.7167553451611159.35366485479784.249718755
#Sta/Elev= 30
       0  654.31    61.1  654.38    87.5  653.64   150.2   652.8   183.2     653
   186.5  652.57   193.1  649.97  204.34647.6864   209.6  646.53   212.9  646.38
   222.8  646.59  228.97647.6884   232.7  648.98   234.7  650.86     236  652.19
   239.3  657.34   242.6   661.4   246.5  664.69   252.5  671.22   259.1  677.38
   265.7   682.3   272.4  686.36     276  688.14   318.7  706.64   328.7  710.27
   348.5  718.51   358.5  722.09   378.4  728.55   411.6  737.05   425.1  739.67
#Mann= 4 ,-1,0
       0     .05       0   192.5      .1       0  204.34    .045       0
  228.97      .1       0
Bank Sta=204.34,228.97
XS Rating Curve= 0 ,0
Exp/Cntr(USF)=0,0
Exp/Cntr=0.3,0.1

Type RM Length L Ch R = 1 ,1203    ,314,302.6,287.9
XS GIS Cut Line= 6
  1610812.984935479458.3471553331610827.97768718479544.553347752
1610840.82838325479618.443948001 1610863.0261735 479716.08450076
1610891.55301934479787.2490565931610927.75373434479869.766936168
#Sta/Elev= 30
       0   653.2    77.7  652.37   137.3  648.51   180.9  648.85   184.3  648.25
  191.91 642.264   194.4  640.99   197.7  640.72   212.1   642.1  235.93642.2653
   241.5  642.89   251.6  649.54   268.7  653.05     297  664.69   299.4   666.8
   305.5  674.31   311.1  679.69   319.6  690.18   322.1   692.7   328.8  696.48
   339.8  700.31     343  702.35   350.1  709.84   353.7   712.7     368  721.43
   378.8  724.74   396.7  724.01   414.6  730.31   421.9  732.14   429.4  732.72
#Mann= 4 ,-1,0
       0     .05       0   157.5      .1       0  191.91    .045       0
  235.93      .1       0
Bank Sta=191.91,235.93
XS Rating Curve= 0 ,0
Exp/Cntr(USF)=0,0
Exp/Cntr=0.3,0.1

Type RM Length L Ch R = 1 ,900     ,293.7,300,306.6
XS GIS Cut Line= 6
1610472.46593101479715.5238063341610533.67807892479778.237919763
1610588.96504185479828.916624174 1610662.6801175479896.489323676
1610717.96675234479947.1686842591610782.46793567480006.294550255
#Sta/Elev= 30
       0  650.77    77.4  648.87   141.1  646.28   154.5  645.42   175.9  645.24
   178.8     645   182.9     644   189.8  639.81   194.1637.7767   198.2  636.91
   207.9  636.69   224.7  637.06   231.3637.7775     237  638.35   240.1  639.31
     249  645.37   253.4  647.41   266.8  651.47   275.9  654.71   285.6  659.97
   302.4  671.33   305.9  672.53   314.7  673.74   319.6   675.6   334.1  685.11
     339   687.8   343.8  689.73   363.3  695.52     378  698.87   425.1  708.19
#Mann= 3 ,-1,0
       0     .05       0   194.1    .045       0   231.3      .1       0
Bank Sta=194.1,231.3
XS Rating Curve= 0 ,0
Exp/Cntr(USF)=0,0
Exp/Cntr=0.3,0.1

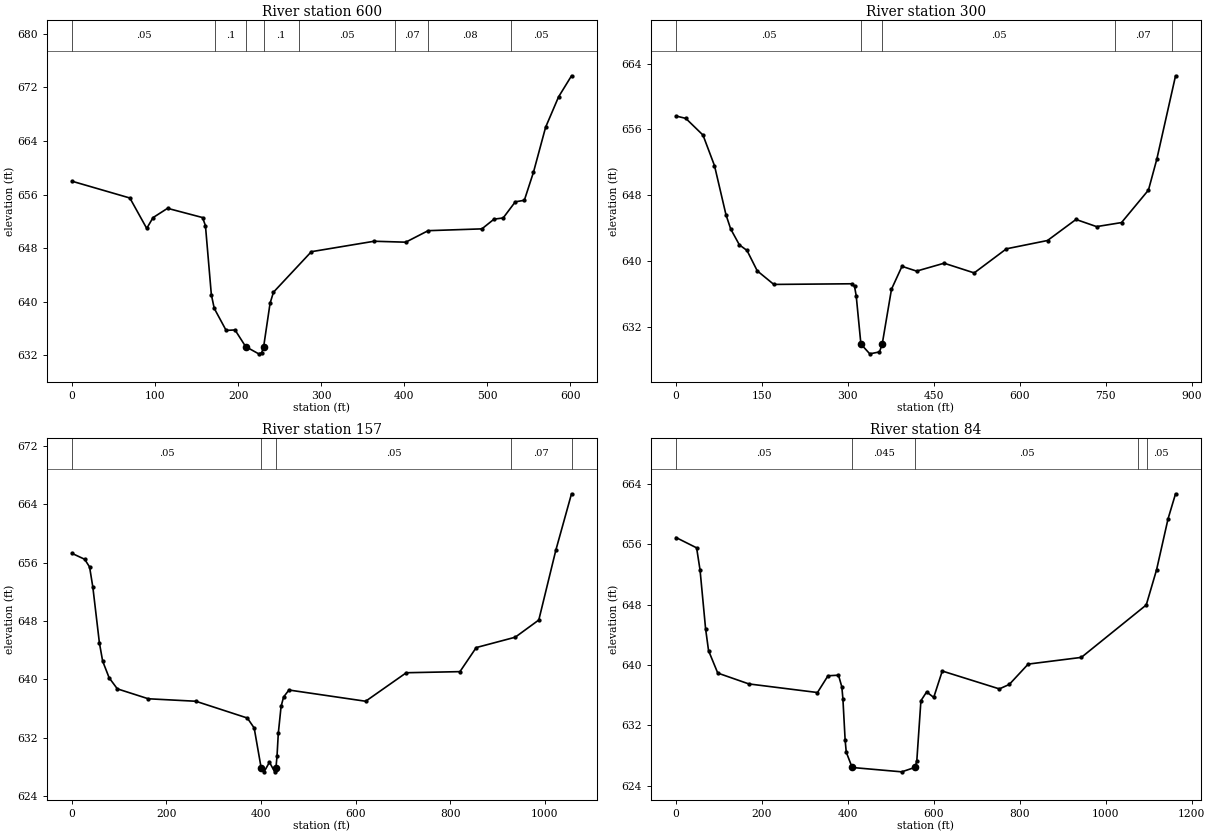
Type RM Length L Ch R = 1 ,600     ,302.6,300,296
XS GIS Cut Line= 6
1610298.33307718479816.7647455931610327.49345192479899.442401752
 1610353.9664961479969.681434512 1610393.0215361480061.739649341
 1610447.9873939480114.2780606891610683.88937957480229.673150574
#Sta/Elev= 30
       0     658    69.7  655.49      90  650.95    97.6  652.56   115.1  653.95
   157.2  652.57   160.7  651.36   167.8  641.05   171.3     639   185.6  635.71
   196.3  635.78  209.11633.2893   224.8  632.21   228.4  632.37  230.78633.2896
   238.5  639.77   242.6  641.42   288.2  647.47   363.7  649.03   401.8  648.89
   428.8  650.61   493.5  650.88   508.1  652.33   519.1  652.51   533.7  654.92
   544.6  655.15   555.6  659.35   570.2  666.06   585.8   670.6   601.4  673.75
#Mann= 8 ,-1,0
       0     .05       0  172.73      .1       0  209.11    .045       0
  230.78      .1       0  272.73     .05       0  388.77     .07       0
  428.77     .08       0  528.77     .05       0
Bank Sta=209.11,230.78
XS Rating Curve= 0 ,0
Exp/Cntr(USF)=0,0
Exp/Cntr=0.3,0.1

Type RM Length L Ch R = 1 ,300     ,141.6,143,144.3
XS GIS Cut Line= 6
1610079.80212285479826.3247172261610039.34967126480039.956556425
1610080.35844751480102.7523625941610135.03812817480186.478901178
1610234.73198179480258.4435432511610557.66113657480408.728285026
#Sta/Elev= 30
       0  657.64    17.1  657.35    47.1  655.32    67.2   651.6    87.2  645.64
    95.4  643.91   110.6  641.97   123.9  641.29   141.8  638.81   170.7  637.16
   307.5  637.24   311.5  636.91   314.4   635.8  322.64629.9069   338.1  628.72
     355  628.95  359.82629.9066     376  636.58   394.3  639.36   419.8  638.78
   467.8  639.74   520.3  638.56   576.5  641.49   648.2   642.5   697.9  645.06
   733.8  644.19   777.3  644.68   824.3  648.63   838.8  652.36   871.6  662.53
#Mann= 5 ,-1,0
       0     .05       0  322.64    .045       0  359.82     .05       0
  765.38     .07       0  865.38     .05       0
Bank Sta=322.64,359.82
XS Rating Curve= 0 ,0
Exp/Cntr(USF)=0,0
Exp/Cntr=0.3,0.1

Type RM Length L Ch R = 1 ,157     ,82.3,73,100.1
XS GIS Cut Line= 5
1610035.50099096479827.3443987411609936.64996187480129.781757651
1610018.94642788480279.6721300291610112.85694694480312.279499123
1610559.57424474480452.661189456
#Sta/Elev= 30
       0  657.28    26.9  656.47    37.3  655.41    44.2  652.64      58  645.03
    64.9  642.51    78.7  640.21      96   638.7   161.5  637.34     262     637
     371   634.7   385.5  633.33  400.35627.8244   406.6  627.34   417.8  628.64
   428.9  627.32   431.4   627.8   433.8  629.46   436.5  632.58   442.4  636.29
   447.7  637.58     459  638.54   621.3     637   707.3  640.91   820.8  641.06
   855.2  644.36   937.7  645.78   987.6  648.14  1023.7  657.73  1056.8  665.45
#Mann= 5 ,-1,0
       0     .05       0  400.35    .045       0   431.4     .05       0
  928.59     .07       0 1056.84     .05       0
Bank Sta=400.35,431.4
XS Rating Curve= 0 ,0
Exp/Cntr(USF)=0,0
Exp/Cntr=0.3,0.1

Type RM Length L Ch R = 1 ,84      ,,,
XS GIS Cut Line= 5
1610028.89895667479814.1403301511609893.66972848480203.061130544
1609960.72266358480324.3698824721610035.28304398480335.386619155
1610554.62271902480470.816783767
#Sta/Elev= 30
       0  656.92      48  655.55      56  652.61    68.9  644.81    75.8  641.91
    97.2  638.94   169.6   637.5   329.2  636.36   353.7  638.58   378.1  638.66
   385.9  637.11   388.4  635.53   393.6  630.04   396.2  628.45  409.91626.4176
   525.3  625.84   556.5  626.44   560.4  627.34   569.9  635.27   583.2  636.44
   599.7  635.71   619.6  639.21   752.4  636.84   775.5  637.43   819.5  640.13
   943.2  641.02  1094.2  647.97  1118.2  652.63    1145  659.41  1162.4  662.72
#Mann= 5 ,-1,0
       0     .05       0  409.91    .045       0   556.5     .05       0
 1075.74     .07       0 1095.74     .05       0
Bank Sta=409.91,556.5
XS Rating Curve= 0 ,0
Exp/Cntr(USF)=0,0
Exp/Cntr=0.3,0.1
LCMann Table=0

Chan Stop Cuts=-1
Use User Specified Reach Order=0
Composite Channel Slope=5